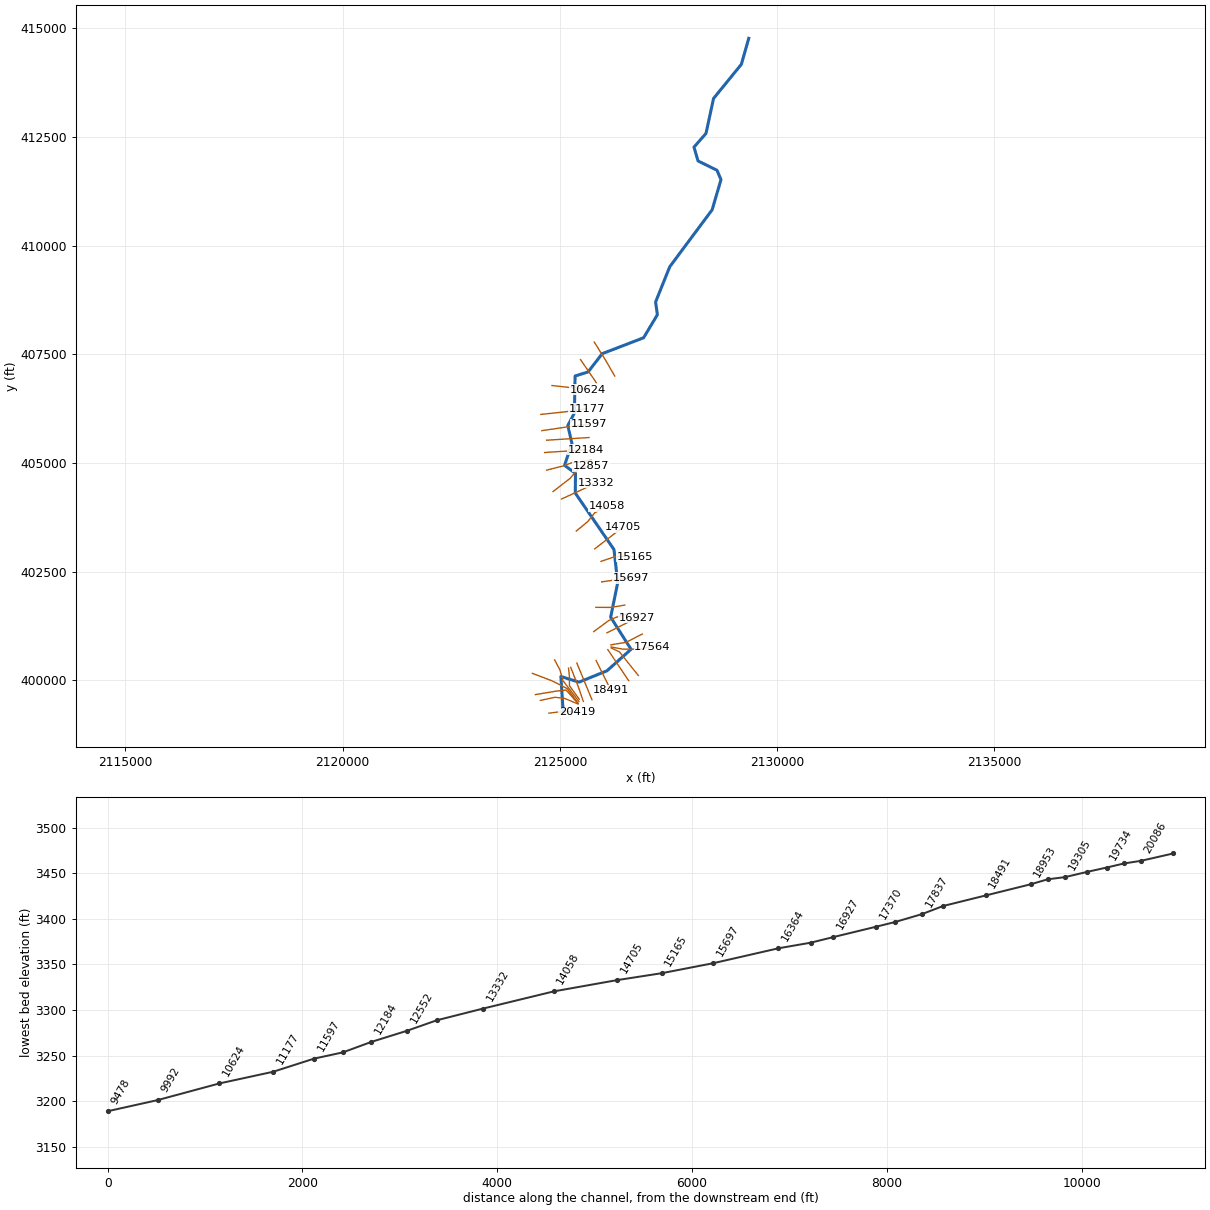
--- COLDKNOBFK.prj (project) ---

Proj Title=COLDKNOBFK
Current Plan=p01
Default Exp/Contr=0,0
English Units
Geom File=g01
Flow File=f01
Plan File=p01
BEGIN DESCRIPTION:
Stream Name- Cold Knob Fork
Flood Zone: Zone A
Greenbrier County, WV
County-Wide Study
WVDHSEM-2018-3, Flood Risk Project
HEC-RAS Version: 5.0.7
General Notes:
For the Hydrology Regression was used.
END DESCRIPTION:
DSS File=dss
DSS Export Rating Curves= 0
DSS Export Rating Curve Sorted= 0
DSS Export Volume Flow Curves= 0
DXF OffsetX= 0
DXF OffsetY= 0
DXF ScaleX= 0
DXF ScaleY= 0

--- COLDKNOBFK.p01 (plan) ---

Plan Title=Floodplain
Program Version=5.07
Short Identifier=Floodplain
Geom File=g01
Flow File=f01
Subcritical Flow
K Sum by GR= 0
Std Step Tol= 0.01
Critical Tol= 0.01
Num of Std Step Trials= 20
Max Error Tol= 0.3
Flow Tol Ratio= 0.001
Split Flow NTrial= 30
Split Flow Tol= 0.02
Split Flow Ratio= 0.02
Log Output Level= 0
Friction Slope Method= 1
Unsteady Friction Slope Method= 2
Unsteady Bridges Friction Slope Method= 1
Parabolic Critical Depth
Global Vel Dist= 0 , 0 , 0
Global Log Level= 0
CheckData=True
Encroach Param=-1 ,0,0, 0
Computation Interval=0.1SEC
Output Interval=1MIN
Instantaneous Interval=Max Profile
Mapping Interval=1HOUR
Computation Time Step Use Courant=        0
Computation Time Step Use Time Series=    0
Computation Time Step Count To Double=0
Computation Time Step Max Doubling=0
Computation Time Step Max Halving=0
Computation Time Step Residence Courant=0
Run HTab= 0
Run UNet= 0
Run Sediment= 0
Run PostProcess= 0
Run WQNet= 0
Run RASMapper= 0
UNET Theta= 0
UNET Theta Warmup= 0
UNET ZTol= 0
UNET ZSATol= 0
UNET MxIter= 0
UNET Max Iter WO Improvement= 0
UNET MaxInSteps= 0
UNET DtIC= 0
UNET DtMin= 0
UNET MaxCRTS= 0
UNET WFStab= 0
UNET SFStab= 0
UNET WFX= 1
UNET SFX= 1
UNET 1D Methodology=Finite Difference
UNET DSS MLevel= 1
UNET Pardiso=0
UNET DZMax Abort= 0
UNET Use Existing IB Tables= 0
UNET Froude Reduction=False
UNET Froude Limit= 0
UNET Froude Power= 0
UNET D1 Cores= 0
UNET D2 Coriolis=0
UNET D2 Cores= 0
UNET D2 Theta= 1
UNET D2 Theta Warmup= 1
UNET D2 Z Tol= 0.01
UNET D2 Volume Tol= 0.01
UNET D2 Max Iterations= 20
UNET D2 Equation= 0
UNET D2 RampUpFraction=0.1
UNET D2 TimeSlices= 1
UNET D2 BCVolumeCheck=0
UNET D1D2 MaxIter= 0
UNET D1D2 ZTol=0.01
UNET D1D2 QTol=0.1
UNET D1D2 MinQTol=1
DSS File=dss
Write IC File= 0
Write IC File at Fixed DateTime=0
Write IC File at Sim End=0
Echo Input=False
Echo Parameters=False
Echo Output=False
Write Detailed= 0
HDF Write Warmup=0
HDF Write Time Slices=0
HDF Flush=0
HDF Face Node Velocities=0
HDF Compression= 1
HDF Chunk Size= 1
HDF Spatial Parts= 1
HDF Use Max Rows=0
HDF Fixed Rows= 1
Calibration Method= 0
Calibration Iterations= 20
Calibration Max Change=0.05
Calibration Tolerance=0.2
Calibration Maximum=1.5
Calibration Minimum=0.5
Calibration Optimization Method= 1
WQ AD Non Conservative
WQ ULTIMATE=-1
WQ Max Comp Step=1HOUR
WQ Output Interval=15MIN
WQ Output Selected Increments= 0
WQ Output face flow=0
WQ Output face velocity=0
WQ Output face area=0
WQ Output face dispersion=0
WQ Output cell volume=0
WQ Output cell surface area=0
WQ Output cell continuity=0
WQ Output cumulative cell continuity=0
WQ Output face conc=0
WQ Output face dconc_dx=0
WQ Output face courant=0
WQ Output face peclet=0
WQ Output face adv mass=0
WQ Output face disp mass=0
WQ Output cell mass=0
WQ Output cell source sink temp=0
WQ Output nsm pathways=0
WQ Output nsm derived pathways=0
WQ Output MaxMinRange=-1
WQ Daily Max Min Mean=-1
WQ Daily Range=0
WQ Daily Time=0
WQ Create Restart=0
WQ Fixed Restart=0
WQ System Summary=0
WQ Write To DSS=0
WQ Use Fixed Temperature=0
Sorting and Armoring Iterations= 10
XS Update Threshold= 0.02
Bed Roughness Predictor= 0
Hydraulics Update Threshold= 0.02
Energy Slope Method= 1
Volume Change Method= 1
Sediment Retention Method= 0
XS Weighting Method= 0
Number of US Weighted Cross Sections= 1
Number of DS Weighted Cross Sections= 1
Upstream XS Weight=0
Main XS Weight=1
Downstream XS Weight=0
Number of DS XS's Weighted with US Boundary= 1
Upstream Boundary Weight= 1
Weight of XSs Associated with US Boundary= 0
Number of US XS's Weighted with DS Boundary= 1
Downstream Boundary Weight= 0.5
Weight of XSs Associated with DS Boundary= 0.5
Percentile Method= 0
Sediment Output Level= 3
Mass or Volume Output= 0
Output Increment Type= 1
Profile and TS Output Increment= 1
XS Output Flag= 0
XS Output Increment= 10
Write Gradation File= 0
Read Gradation Hotstart= 0
Write HDF5 File= 1
Write Binary Output= 1
Write DSS Sediment File= 0
SV Curve= 0
Specific Gage Flag= 0

--- COLDKNOBFK.f01 (steady flow) ---

Flow Title=NFF Regression Equation
Program Version=5.07
Number of Profiles= 6
Profile Names=f1p,f10p,f4p,f2p,f02p,f1pplus
River Rch & RM=COLDKNOBFK,Main            ,20419
     522     275     366     441     730     772
River Rch & RM=COLDKNOBFK,Main            ,19529
     611     323     430     517     852     903
River Rch & RM=COLDKNOBFK,Main            ,17370
     788     422     557     669    1090    1170
River Rch & RM=COLDKNOBFK,Main            ,15165
     944     509     670     803    1310    1400
River Rch & RM=COLDKNOBFK,Main            ,9992
    1310     714     935    1120    1800    1930
River Rch & RM=COLDKNOBFK,Main            ,7683
    1460     800    1040    1250    2000    2160
River Rch & RM=COLDKNOBFK,Main            ,4939
    1720     948    1240    1470    2350    2540
Boundary for River Rch & Prof#=COLDKNOBFK,Main            , 1
Up Type= 0
Dn Type= 3
Dn Slope=0.02018
Boundary for River Rch & Prof#=COLDKNOBFK,Main            , 2
Up Type= 0
Dn Type= 3
Dn Slope=0.02018
Boundary for River Rch & Prof#=COLDKNOBFK,Main            , 3
Up Type= 0
Dn Type= 3
Dn Slope=0.02018
Boundary for River Rch & Prof#=COLDKNOBFK,Main            , 4
Up Type= 0
Dn Type= 3
Dn Slope=0.02018
Boundary for River Rch & Prof#=COLDKNOBFK,Main            , 5
Up Type= 0
Dn Type= 3
Dn Slope=0.02018
Boundary for River Rch & Prof#=COLDKNOBFK,Main            , 6
Up Type= 0
Dn Type= 3
Dn Slope=0.02018
DSS Import GetInterval= 0
DSS Import GetPeak= 0
DSS Import FillOption= 0

--- COLDKNOBFK.g01 (geometry) ---

Geom Title=USGS 10m DEM
Program Version=5.07

River Reach=COLDKNOBFK      ,Main
Reach XY= 30
     2125077.369      399234.813     2125023.062      400083.162
     2125441.229      399953.943     2126083.733      400214.788
      2126637.47      400709.752     2126168.525      401449.553
     2126330.647      402243.337     2126245.851      403004.289
     2125354.171      404305.496     2125359.121      404758.218
     2125107.068      404943.512     2125277.129      405446.077
     2125182.887      405860.825      2125333.97      406148.176
     2125349.866      406999.286     2125648.842      407093.574
      2125973.57      407513.581     2126926.698      407880.536
      2127244.97      408411.413     2127201.809      408701.233
     2127528.778      409515.397      2128503.99      410825.359
     2128707.741       411518.96     2128616.645      411735.181
     2128180.163      411949.497     2128085.799      412267.587
     2128362.454      412582.986     2128536.806      413388.651
     2129177.401       414174.852129346.77546005 414772.06469658

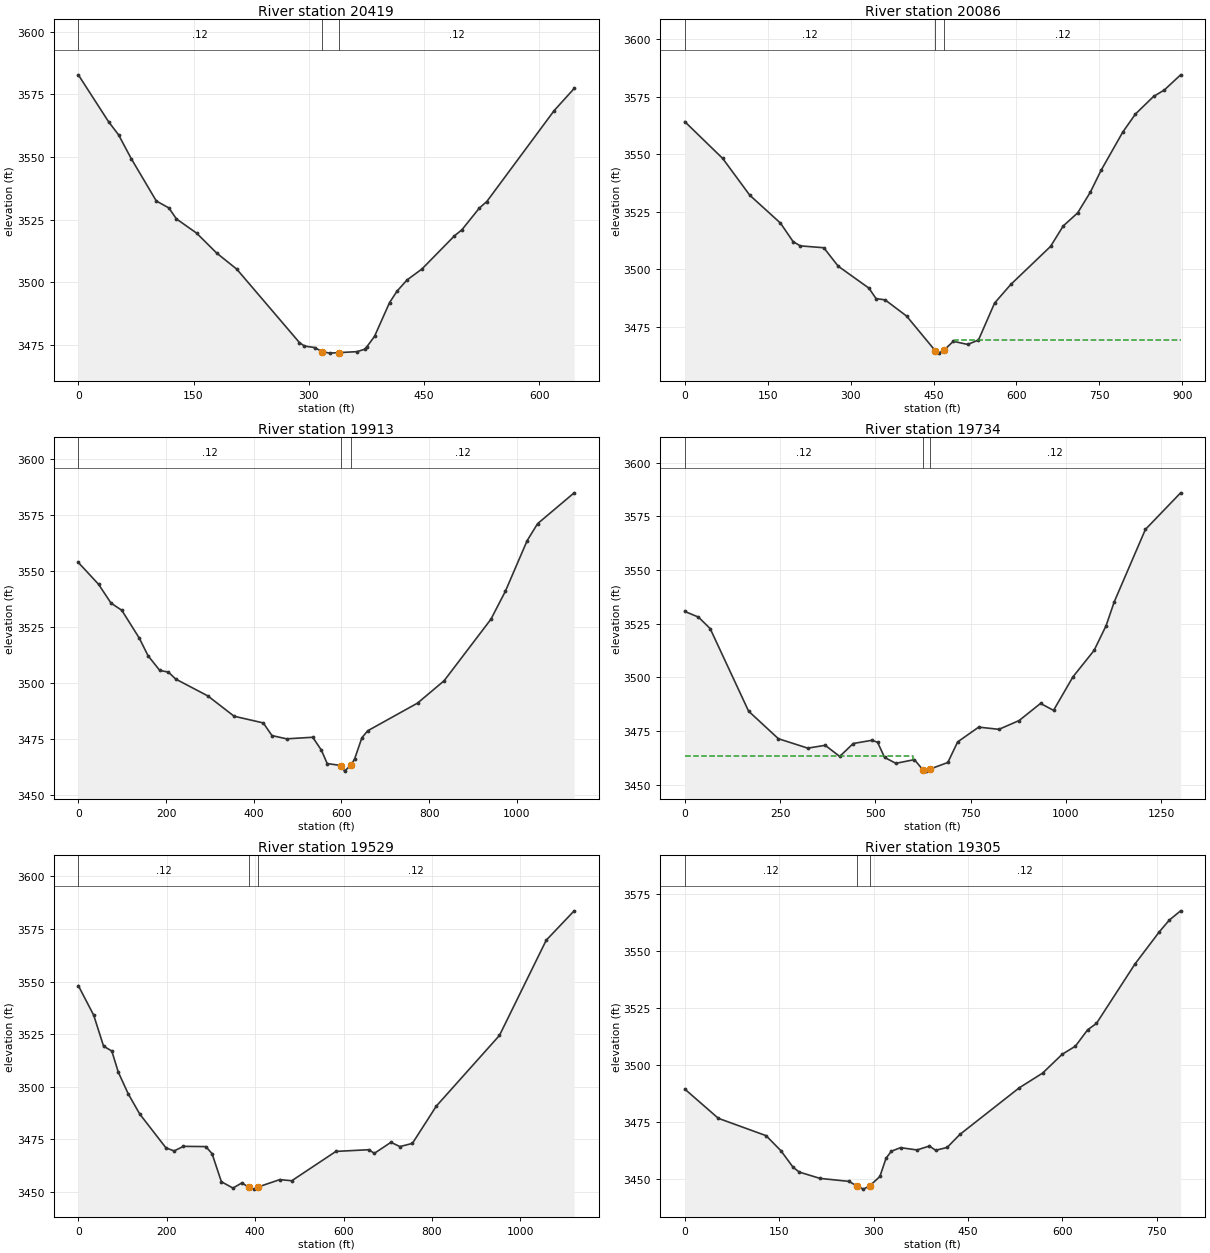
Type RM Length L Ch R = 1 ,20419   ,332.6,332.6,332.6
XS GIS Cut Line= 4
     2124746.724      399239.817     2124983.957      399269.471
     2125169.295      399279.356      2125389.23      399259.586
#Sta/Elev= 30
       0 3582.81    39.3 3564.12    52.4 3558.85    68.8  3549.4   101.5 3532.46
   117.9 3529.67   127.7  3525.3   153.9 3519.64   180.1 3511.67   206.3 3505.23
   287.9 3475.92   294.4 3474.54   307.5 3473.96   317.2 3472.36     327 3471.72
   339.7 3471.93   362.8 3472.31   372.6 3473.25   375.8 3474.33   385.6 3478.41
   405.1 3491.85   414.9 3496.46   427.9 3500.92   447.4 3505.32   489.6 3518.52
   499.4 3520.97   522.1 3529.64   531.8 3532.24   619.5 3568.55   645.5 3577.36
#Mann= 3 ,-1 , 0
       0     .12       0   317.2     .04       0   339.7     .12       0
Bank Sta=317.2,339.7
XS Rating Curve= 0 ,0
Exp/Cntr=0.3,0.1

Type RM Length L Ch R = 1 ,20086   ,173.7,173.7,173.7
XS GIS Cut Line= 4
     2124551.501      399533.887     2124890.052      399605.551
     2125112.458      399578.368     2125413.942      399452.338
#Sta/Elev= 30
       0  3564.2    68.6  3548.2   117.5 3532.24     173 3520.13   195.9 3512.08
   208.9 3510.22   251.4 3509.41   277.5 3501.39     333 3491.87     346  3487.3
   362.3 3486.76   401.3  3479.7   453.2 3464.61   459.7 3463.61   469.4 3465.03
   485.7 3468.74   511.7 3467.39   531.2 3469.29   560.4 3485.38   589.7 3493.46
   661.6 3509.98   684.5 3518.86   710.6 3524.55   733.5 3533.52   753.1 3543.09
   792.3 3559.69   815.2 3567.52   847.9 3575.14   867.5 3577.97   896.9 3584.55
#Mann= 3 ,-1 , 0
       0     .12       0   453.2     .04       0   469.4     .12       0
#XS Ineff= 2 , 0
                          488.04         3469.35
Permanent Ineff=
       F       F
Bank Sta=453.2,469.4
XS Rating Curve= 0 ,0
Exp/Cntr=0.3,0.1

Type RM Length L Ch R = 1 ,19913   ,178.3,178.3,178.3
XS GIS Cut Line= 4
 2124434.9376302  399666.74014082124926.47103426399748.662374811
2125145.61301024399771.1909891642125416.93936188399460.708877981
#Sta/Elev= 30
       0 3553.83    46.1  3544.1    74.6 3535.68    99.2 3532.48   139.1 3520.05
     159 3512.22   185.6 3505.68   205.6 3504.88   222.2 3501.79   295.4 3494.28
   355.3 3485.22   421.8 3482.23   441.7 3476.58     475 3475.13   534.6 3475.83
   554.4 3470.08   567.6  3464.1   599.33463.222   607.2 3460.72   621.9 3463.41
   630.2 3466.18   646.7 3475.59   659.9 3478.71   773.7 3491.08   834.3 3501.05
   941.1 3528.52   973.9 3540.94  1023.7 3563.58  1047.5 3571.14  1130.9  3584.9
#Mann= 3 , 0 , 0
       0     .12       0   599.3     .04       0   621.9     .12       0
Bank Sta=599.3,621.9
XS Rating Curve= 0 ,0
Exp/Cntr(USF)=0,0
Exp/Cntr=0.3,0.1

Type RM Length L Ch R = 1 ,19734   ,205.2,205.2,205.2
XS GIS Cut Line= 4
2124365.58256091400156.2230830362124824.34707137399982.138335762
2125168.42045422399806.0055326382125421.57795148399466.008328884
#Sta/Elev= 30
       0 3530.72    35.6  3528.1    66.5 3522.74   167.4 3484.23   245.5 3471.38
   322.7 3466.98   368.5  3468.3   406.5 3463.11     442 3469.14   490.7 3470.63
   505.9 3469.72   524.3 3462.63   553.9  3459.9   602.6 3461.62   624.5 3456.92
   631.8 3456.26   642.2 3457.14   690.2 3460.29     716 3469.89   771.2 3476.78
   824.4 3475.75   877.2 3479.84   933.5 3487.82   967.6  3484.6  1018.7 3500.26
    1074 3512.54  1105.5 3524.06  1127.1 3535.29  1208.6 3568.93  1301.1 3586.02
#Mann= 3 , 0 , 0
       0     .12       0   624.5     .04       0   642.2     .12       0
#XS Ineff= 2 , 0
          599.57 3463.29
Permanent Ineff=
       F       F
Bank Sta=624.5,642.2
XS Rating Curve= 0 ,0
Exp/Cntr(USF)=0,0
Exp/Cntr=0.3,0.1

Type RM Length L Ch R = 1 ,19529   ,224.5,224.5,224.5
XS GIS Cut Line= 4
2124878.43331968400466.3949120672124999.08742332  400238.4927163
2125071.14473522399987.1300003812125438.13430046399509.540840134
#Sta/Elev= 30
       0 3548.11    34.8 3534.04    57.1 3519.32    75.7 3517.03    90.5 3506.95
   112.8 3496.71   138.8 3487.11   198.2    3471   216.7 3469.53   237.9 3471.71
   288.3 3471.59   302.4 3468.29   323.6  3454.9   349.8 3451.87   370.2 3454.34
   385.2 3452.25   397.5 3451.37   406.5 3452.37   455.6 3455.89   482.9 3455.36
   582.7  3469.3   657.2 3470.11   669.6 3468.38   707.3 3473.63   727.5 3471.59
   755.7 3473.11     810 3490.88   952.7 3524.44  1058.5  3569.7  1121.7 3583.67
#Mann= 3 , 0 , 0
       0     .12       0   385.2     .04       0   406.5     .12       0
Bank Sta=385.2,406.5
XS Rating Curve= 0 ,0
Exp/Cntr(USF)=0,0
Exp/Cntr=0.3,0.1

Type RM Length L Ch R = 1 ,19305   ,175.2,175.2,175.2
XS GIS Cut Line= 4
2125198.50184462400275.3592479682125220.28661333400069.241820914
2125220.28661333399869.8273996182125444.83730622399561.489134757
#Sta/Elev= 30
       0 3489.57    53.3 3476.75   129.2 3469.15   152.9  3462.5   172.1  3455.3
     182 3453.18   214.9 3450.42   260.9  3449.1  274.22 3446.99   283.8 3445.71
   293.7 3447.09   310.1 3451.25   319.9 3459.28   328.3 3462.32   342.9 3463.89
   369.1 3462.88   388.8  3464.6   398.7 3462.73     417 3463.99   437.3  3469.7
   531.7 3490.14   568.7 3496.56   599.7 3504.78   620.9 3508.39   640.3 3515.55
   654.3 3518.34   715.6 3544.42   754.2 3558.49   770.1 3563.64   788.1  3567.7
#Mann= 3 , 0 , 0
       0     .12       0  274.22     .04       0   293.7     .12       0
Bank Sta=274.22,293.7
XS Rating Curve= 0 ,0
Exp/Cntr(USF)=0,0
Exp/Cntr=0.3,0.1

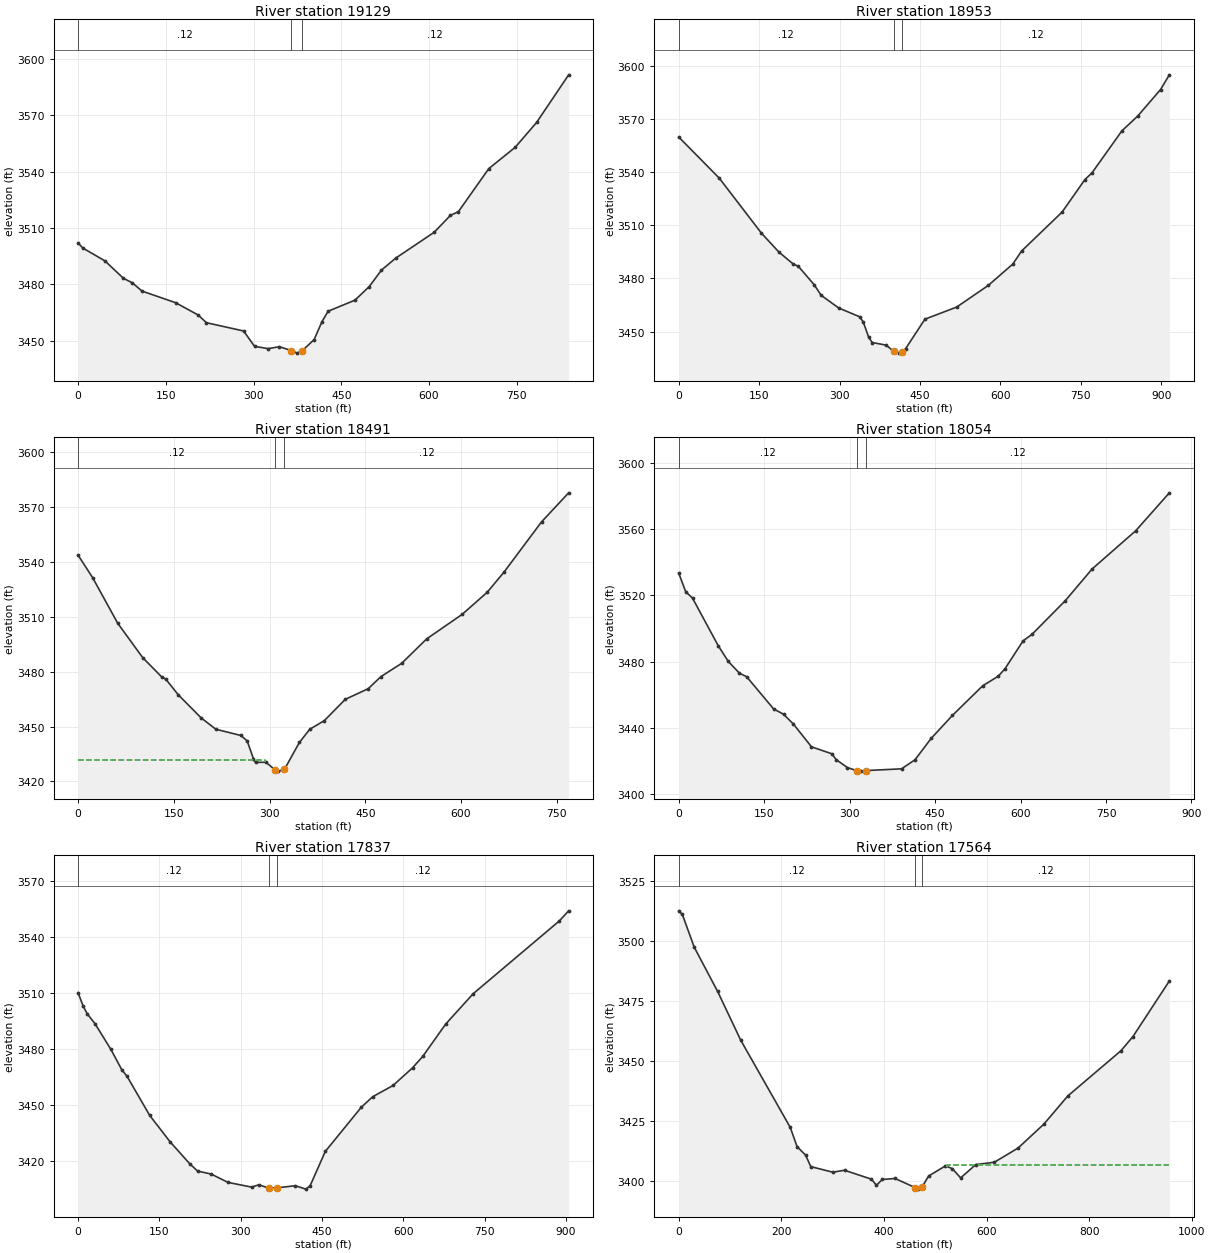
Type RM Length L Ch R = 1 ,19129   ,177,177,177
XS GIS Cut Line= 3
2125248.29463238400295.4908808542125430.57160305399830.582202842
2125539.11856312399509.037434349
#Sta/Elev= 30
       0 3502.08     8.1 3499.37    46.1 3492.48    77.6 3483.22    92.7 3480.84
   109.4 3476.42   166.7 3470.25   205.2  3463.7   219.5 3459.58     283 3455.17
   301.7 3446.98   325.2 3445.75   344.3 3446.81     364 3444.76   374.6 3443.37
   382.8 3444.54   403.6  3450.6   416.9 3460.08   427.4 3465.68   473.3 3471.58
   497.9 3478.86   518.7 3487.62   543.2 3494.02   608.8 3507.76   636.4 3516.71
   650.3 3518.79   702.2  3541.7   747.3 3553.03     784 3566.33   838.7 3591.66
#Mann= 3 , 0 , 0
       0     .12       0     364     .04       0   382.8     .12       0
Bank Sta=364,382.8
XS Rating Curve= 0 ,0
Exp/Cntr(USF)=0,0
Exp/Cntr=0.3,0.1

Type RM Length L Ch R = 1 ,18953   ,462,462,462
XS GIS Cut Line= 2
     2125389.605      400394.377     2125738.193      399548.037
#Sta/Elev= 30
       0 3559.68    75.5 3536.54   154.2 3505.52     187  3494.8   213.2 3488.19
   223.1  3486.8   252.6 3476.44   265.7 3470.45   298.5  3463.3   337.9  3458.3
   344.5  3455.2   354.3 3446.82   360.9 3443.84   387.1 3442.35   401.1 3438.81
   410.1 3437.86   416.6 3438.47   423.2 3440.36   459.3 3457.02   518.4 3463.81
   577.4 3476.02   623.3 3488.11   639.7 3495.46   715.2  3517.4   757.8 3535.73
     771 3539.51   826.7 3563.16   856.3 3571.54   898.9 3586.49   915.3 3594.78
#Mann= 3 ,-1 , 0
       0     .12       0   401.1     .04       0   416.6     .12       0
Bank Sta=401.1,416.6
XS Rating Curve= 0 ,0
Exp/Cntr=0.3,0.1

Type RM Length L Ch R = 1 ,18491   ,436.8,436.8,436.8
XS GIS Cut Line= 2
     2125833.852      400452.745     2126174.333      399763.676
#Sta/Elev= 30
       0 3543.68    22.9 3531.34    62.1 3506.47   101.4  3487.6   130.8  3477.2
   137.4 3475.91     157 3467.34     193 3454.67   215.9 3448.51   255.1  3445.1
   264.9 3442.16   274.7 3432.43     278 3430.38   294.4 3430.46   308.4 3426.34
     314 3425.61   323.4 3426.62   346.7 3441.27     363  3448.5   385.9 3453.24
   418.6 3464.86   454.6 3470.68   474.2 3477.21     507 3484.56   546.2 3497.93
   601.8 3511.33     641  3523.4   667.2 3534.36   726.1 3561.88   768.6 3577.77
#Mann= 3 ,-1 , 0
       0     .12       0   308.4     .04       0   323.4     .12       0
#XS Ineff= 2 , 0
          293.04 3431.51
Permanent Ineff=
       F       F
Bank Sta=308.4,323.4
XS Rating Curve= 0 ,0
Exp/Cntr=0.3,0.1

Type RM Length L Ch R = 1 ,18054   ,217.1,217.1,217.1
XS GIS Cut Line= 2
2126103.46304722400701.1987106242126583.37904722399986.187710624
#Sta/Elev= 30
       03533.375  12.297  3522.2  24.1193518.425  69.0423489.828  86.7533480.305
  106.513473.129 119.1873470.999 166.2823451.656 183.9433448.347 201.3423442.412
 232.9533428.727 268.5153424.547 276.4173420.975 296.1743416.171 313.457 3414.27
 319.8823414.065 329.123 3414.41 391.0063415.446 414.7143420.919  442.973433.781
 480.4433447.699 533.255 3465.46 560.9143471.341 572.6543475.842 604.3793492.634
 619.9413496.521 678.4493516.863 725.5453535.987 801.9463558.992 861.1393581.918
#Mann= 3 ,-1 , 0
       0     .12       0 313.457     .04       0 329.123     .12       0
Bank Sta=313.457,329.123
XS Rating Curve= 0 ,0
Exp/Cntr=0.3,0.1

Type RM Length L Ch R = 1 ,17837   ,272.6,272.6,272.6
XS GIS Cut Line= 4
 2126180.9709418400741.1156670762126370.88943827400649.880310928
2126581.28934123400385.4839727022126804.72286649 400108.05401217
#Sta/Elev= 30
       0  3510.4     9.5 3503.13    16.8 3499.14    31.3 3493.75    60.5 3480.05
    80.5 3469.17    90.3 3465.62   132.1 3444.66   169.7 3430.52   206.1 3418.71
   220.4 3414.85   245.6 3413.24   276.2 3408.81   319.9 3406.25   333.6  3407.5
   351.6 3405.72   367.1 3405.88   400.7 3406.99   420.1 3405.17   427.9 3406.93
     456 3425.38   522.3 3449.01   543.2 3454.63   581.1 3460.72     617 3470.19
   635.7 3476.27     678 3493.58   728.6 3509.82   887.7 3548.86   904.8 3554.25
#Mann= 3 , 0 , 0
       0     .12       0   351.6     .04       0   367.1     .12       0
Bank Sta=351.6,367.1
XS Rating Curve= 0 ,0
Exp/Cntr(USF)=0,0
Exp/Cntr=0.3,0.1

Type RM Length L Ch R = 1 ,17564   ,193.6,193.6,193.6
XS GIS Cut Line= 4
2126182.83288784400763.4590196022126445.36728003400713.186476418
2126810.30870462400711.3245303742127128.70147811400772.768749821
#Sta/Elev= 30
       0 3512.49     6.9    3511    30.2 3497.33    75.7 3478.95   120.9 3458.59
   217.3 3422.35   230.7  3414.3   247.4 3410.76   257.4 3405.99   300.2 3403.68
   323.2 3404.47   375.7 3400.76   385.5 3398.23   396.7 3400.63   421.6 3401.05
     461 3397.26   466.6 3396.62   474.1 3397.41   487.2  3402.1     520 3406.29
   533.2 3405.16   549.6 3401.31   579.1 3406.84   615.4 3407.82   661.7 3413.75
   711.8 3423.68   758.6 3435.43   862.1 3454.23   885.5 3460.14   956.5 3483.29
#Mann= 3 , 0 , 0
       0     .12       0     461     .04       0   474.1     .12       0
#XS Ineff= 2 , 0
                          523.39         3406.64
Permanent Ineff=
       F       F
Bank Sta=461,474.1
XS Rating Curve= 0 ,0
Exp/Cntr(USF)=0,0
Exp/Cntr=0.3,0.1

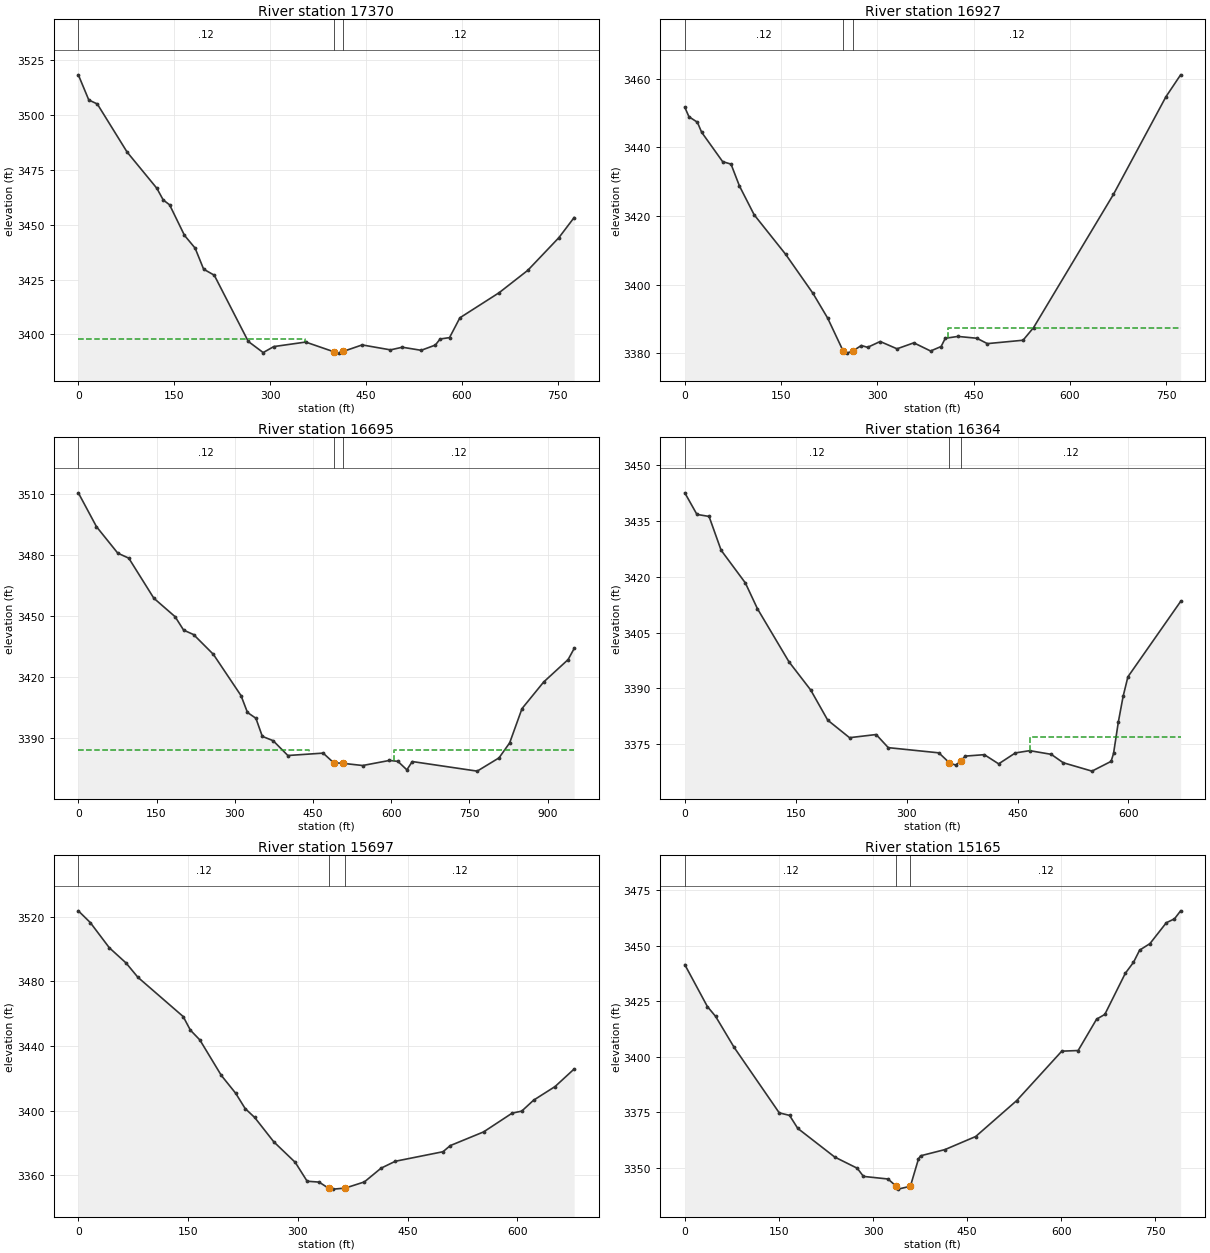
Type RM Length L Ch R = 1 ,17370   ,443,443,443
XS GIS Cut Line= 3
2126173.42699404400812.142369342     2126527.785       400871.05
      2126897.45      401062.368
#Sta/Elev= 30
       03518.259  16.3663506.795  29.6693504.982  76.2313483.089 122.7933466.574
 132.771 3461.26 142.7483459.037 166.0293445.118 182.6593439.306 195.9623429.723
 212.5913426.982 265.8053396.804 289.0863391.733 305.7153394.466 355.6033396.517
 399.5333392.106 406.921 3391.48 414.3093392.253 443.8633395.221 488.1933392.963
 506.6643394.166 536.2183392.765 558.3833395.158 565.7713397.916 580.5483398.544
 596.727 3407.57 658.1263419.006 702.9133429.194 751.5993444.096  775.463453.258
#Mann= 3 ,-1 , 0
       0     .12       0 399.533     .04       0 414.309     .12       0
#XS Ineff= 2 , 0
           354.9 3397.88
Permanent Ineff=
       F       F
Bank Sta=399.533,414.309
XS Rating Curve= 0 ,0
Exp/Cntr=0.3,0.1

Type RM Length L Ch R = 1 ,16927   ,232.3,232.3,232.3
XS GIS Cut Line= 2
     2126083.538      401089.931     2126774.229      401435.276
#Sta/Elev= 30
       0  3451.7     6.5 3448.94    19.6 3447.34    26.2 3444.43    58.9 3435.86
      72 3435.12    85.1 3428.76     108 3420.36   157.1 3408.82   199.6 3397.45
   222.5 3390.23   246.3 3380.77     252 3380.02   261.3  3380.6   274.9 3382.24
   284.7 3381.71   304.3 3383.41   330.5 3381.28   356.7 3383.02   382.8 3380.64
   399.2 3381.95   405.7 3384.35   425.4 3384.89   454.8 3384.36   471.2 3382.79
   526.8 3383.78   543.2 3387.47   667.5 3426.28   749.3 3454.76   772.2 3461.16
#Mann= 3 ,-1 , 0
       0     .12       0   246.3     .04       0   261.3     .12       0
#XS Ineff= 2 , 0
                           409.3         3387.44
Permanent Ineff=
       F       F
Bank Sta=246.3,261.3
XS Rating Curve= 0 ,0
Exp/Cntr=0.3,0.1

Type RM Length L Ch R = 1 ,16695   ,331.2,331.2,331.2
XS GIS Cut Line= 5
2125777.74512632401115.7019201482126126.71797307401373.183758386
2126279.63865872401439.8414931582126563.26078511401533.946530484
2126610.31330377   401554.858761
#Sta/Elev= 30
       0 3510.63    34.8    3494    75.7 3480.97    96.7 3478.54   144.8 3458.85
   185.6 3449.76   201.9 3443.18   221.1 3440.97     259 3431.26     312 3410.99
   324.3 3402.72   340.5 3399.87   352.8 3390.97   373.6 3388.84   401.8 3381.56
   469.5 3382.74   489.5 3378.03   508.1  3377.7   545.2 3376.65   596.6 3379.14
   612.8 3378.68     630 3374.53   640.4  3378.6   764.9 3373.89   806.7  3380.4
   827.1 3387.76   850.8 3404.62   892.4  3417.7   939.2  3428.7   950.8 3434.15
#Mann= 3 ,-1 , 0
       0     .12       0   489.5     .04       0   508.1     .12       0
#XS Ineff= 2 , 0
          442.42 3384.14  605.19          3384.5
Permanent Ineff=
       F       F
Bank Sta=489.5,508.1
XS Rating Curve= 0 ,0
Exp/Cntr=0.3,0.1

Type RM Length L Ch R = 1 ,16364   ,667.1,667.1,667.1
XS GIS Cut Line= 4
     2125827.367      401675.235     2126148.392      401673.613
     2126282.963      401691.448     2126493.737      401727.117
#Sta/Elev= 30
       0 3442.64    16.4 3436.83    32.8 3436.29    49.1  3427.2    81.9 3418.39
    98.3 3411.43   140.9 3397.16   170.3 3389.57   193.3 3381.46   222.8 3376.74
   258.8 3377.59   275.2 3374.06   343.6 3372.66     358 3369.96   366.3 3369.37
     373 3370.37   379.2 3371.78   405.1 3372.17   424.5  3369.7   447.1 3372.64
   466.5 3373.25   495.6 3372.26   511.8    3370   550.7 3367.74   576.6 3370.37
   579.9 3372.52   586.3 3380.89   592.8 3387.85   599.3 3393.12   670.6 3413.41
#Mann= 3 ,-1 , 0
       0     .12       0     358     .04       0     373     .12       0
#XS Ineff= 2 , 0
                          467.27         3376.82
Permanent Ineff=
       F       F
Bank Sta=358,373
XS Rating Curve= 0 ,0
Exp/Cntr=0.3,0.1

Type RM Length L Ch R = 1 ,15697   ,532,532,532
XS GIS Cut Line= 3
     2125962.078      402261.423     2126377.977      402321.473
     2126633.744      402350.386
#Sta/Elev= 30
       0 3523.66    16.3 3516.42    42.4 3500.78    65.2  3491.4    81.4 3482.54
   143.3 3458.24   153.1 3449.85   166.1 3443.75   195.4 3421.82     215 3410.79
     228  3401.3     241 3395.79   267.1 3380.73   296.4 3368.03   312.7 3356.34
     329  3355.8     342    3352   348.6 3351.45   364.8  3352.1   390.9 3355.91
   413.7 3364.41   433.2 3368.69   498.4  3374.6   508.2 3378.37   553.8 3386.85
   592.9 3398.48   605.9 3399.71   622.2  3406.5   651.5 3414.92   677.6 3425.79
#Mann= 3 ,-1 , 0
       0     .12       0     342     .04       0   364.8     .12       0
Bank Sta=342,364.8
XS Rating Curve= 0 ,0
Exp/Cntr=0.3,0.1

Type RM Length L Ch R = 1 ,15165   ,459.5,459.5,459.5
XS GIS Cut Line= 4
     2125946.509      402732.924     2126231.189      402830.782
     2126362.408      402853.023     2126718.258      402841.903
#Sta/Elev= 30
       0 3441.53      36 3422.64    49.1 3418.22    78.5 3404.32   150.5 3374.78
   166.9 3373.64     180 3367.79   238.9 3354.88   274.8 3349.84   284.7 3346.16
   323.8 3344.99   336.7 3341.79     340 3340.43   359.5 3341.74   372.4 3354.06
   375.7 3355.44   414.6 3358.24   463.5 3364.12   528.8 3380.28   600.7 3402.56
   626.8 3402.85   656.2 3416.97   669.3 3419.11     702 3437.65     715 3442.57
   724.8 3448.07   741.2 3450.99   767.3  3460.4   780.3 3462.15   790.1 3465.76
#Mann= 3 ,-1 , 0
       0     .12       0   336.7     .04       0   359.5     .12       0
Bank Sta=336.7,359.5
XS Rating Curve= 0 ,0
Exp/Cntr=0.3,0.1

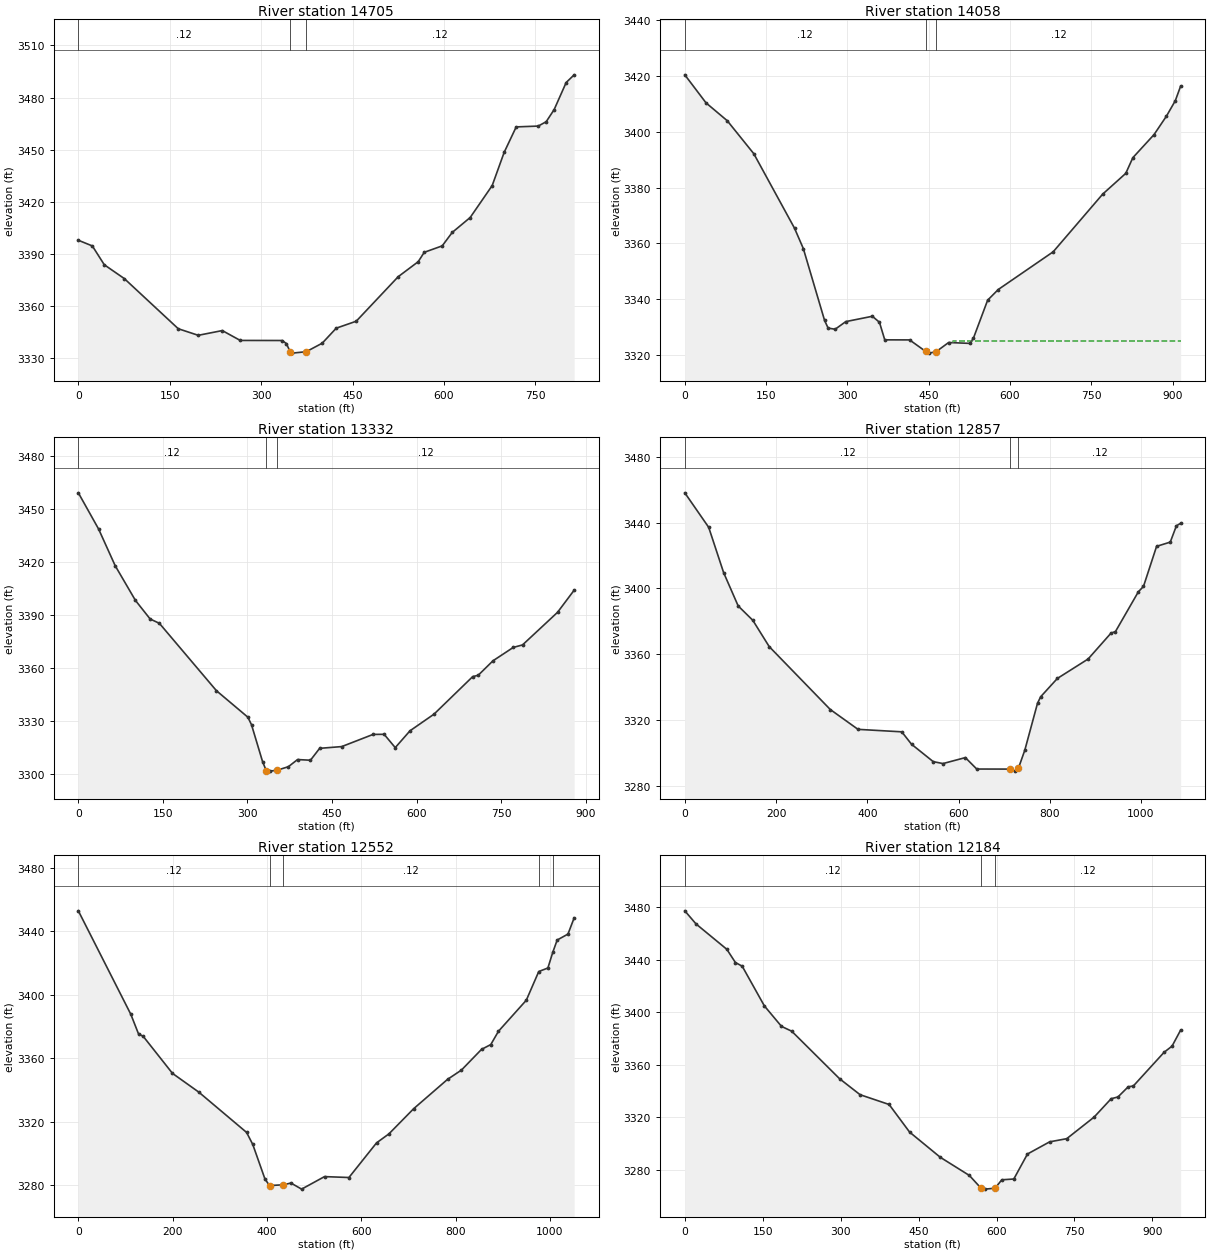
Type RM Length L Ch R = 1 ,14705   ,647.6,647.6,647.6
XS GIS Cut Line= 2
     2125801.946      403022.052     2126446.923      403518.017
#Sta/Elev= 30
       0 3397.83      23 3394.55    42.6 3383.71    75.5 3375.74     164 3346.87
   196.8 3343.09   236.2 3345.82   265.7 3340.14   334.6  3340.1   341.2 3338.37
   347.8 3333.59     351 3332.83     374 3333.65   400.2 3338.55   423.2  3347.2
     456  3351.2   524.9 3376.85   557.7 3385.48   567.6 3390.88   597.1  3394.6
   613.5 3402.32     643 3410.93   679.1 3429.32   698.8 3448.49   718.5  3463.1
   754.6 3463.58   767.7 3466.08   780.8 3473.09   800.5 3488.67   813.6 3493.09
#Mann= 3 ,-1 , 0
       0     .12       0   347.8     .04       0     374     .12       0
Bank Sta=347.8,374
XS Rating Curve= 0 ,0
Exp/Cntr=0.3,0.1

Type RM Length L Ch R = 1 ,14058   ,726.2,726.2,726.2
XS GIS Cut Line= 4
      2125377.15      403431.279     2125644.037       403651.46
     2125797.497      403847.178     2126073.281      404009.534
#Sta/Elev= 30
       0 3420.47    39.2 3410.39    78.3 3403.99   127.3 3392.14   202.4 3365.39
   218.7 3358.05   257.9 3332.24   264.4 3329.51   277.4  3329.1     297 3331.84
     346 3333.76   359.1  3331.6   368.9 3325.29   414.7 3325.27   444.2 3321.16
   450.7 3320.52   463.8 3321.06   486.7 3324.33     526 3324.02   532.5 3325.91
   558.7 3339.54   578.3 3343.37   679.6 3356.91     771 3377.64   813.5 3385.08
   826.6 3390.72   865.7 3399.01   888.6 3405.65   904.9 3411.18   914.7 3416.41
#Mann= 3 ,-1 , 0
       0     .12       0   444.2     .04       0   463.8     .12       0
#XS Ineff= 2 , 0
                          494.46         3324.85
Permanent Ineff=
       F       F
Bank Sta=444.2,463.8
XS Rating Curve= 0 ,0
Exp/Cntr=0.3,0.1

Type RM Length L Ch R = 1 ,13332   ,474.6,474.6,474.6
XS GIS Cut Line= 3
     2125034.645      404167.442     2125495.025      404378.728
     2125830.858      404541.084
#Sta/Elev= 30
       0 3458.97      36 3438.48    65.4 3417.76   101.3 3398.17   127.4 3387.66
   143.8 3385.21   245.1  3347.1   300.7 3332.18   307.2 3327.91   326.8  3307.1
   333.3 3301.98   339.9 3301.68     353 3302.23   372.6 3304.18   388.9 3308.22
   411.8 3307.84   428.1 3314.56   467.3 3315.55   522.9 3322.43   542.5 3322.49
   562.2 3314.96   588.4 3324.48   630.9 3333.86   699.6 3355.09   709.4 3355.86
   735.6 3364.04   771.6  3371.6     788 3373.01   850.1 3391.43   879.6 3403.95
#Mann= 3 ,-1 , 0
       0     .12       0   333.3     .04       0     353     .12       0
Bank Sta=333.3,353
XS Rating Curve= 0 ,0
Exp/Cntr=0.3,0.1

Type RM Length L Ch R = 1 ,12857   ,304.7,304.7,304.7
XS GIS Cut Line= 4
2124842.70228406404340.174823773 2125233.2095038404643.590505295
2125441.10543373404876.7710753542125716.42707066404927.340355608
#Sta/Elev= 30
       0 3458.13    52.4 3437.14    85.1 3409.61     117 3389.34   149.1  3380.6
     185 3364.62   318.9 3326.35   379.7 3314.28   475.6 3312.77     497 3305.23
   544.6 3294.64     566 3293.47     615  3297.1     640 3290.14   713.9 3290.11
   724.9 3288.87   731.3  3290.6   745.3 3301.57   773.2 3330.17   780.1  3334.1
   816.7 3345.24   884.1 3357.06   934.1 3372.74   944.1 3373.77   994.2 3397.92
  1005.5 3401.22  1034.2 3425.57  1064.2 3428.16  1077.6 3438.05  1086.9 3439.61
#Mann= 3 , 0 , 0
       0     .12       0   713.9     .04       0   731.3     .12       0
Bank Sta=713.9,731.3
XS Rating Curve= 0 ,0
Exp/Cntr(USF)=0,0
Exp/Cntr=0.3,0.1

Type RM Length L Ch R = 1 ,12552   ,368.6,368.6,368.6
XS GIS Cut Line= 4
     2124694.364      404832.436      2125059.11      404925.846
     2125272.619      405001.464     2125717.431       405059.29
#Sta/Elev= 30
       0 3453.04   111.3 3387.75   127.7 3375.33   137.5 3373.87   199.7 3350.45
   255.4 3338.64   356.9 3313.18     370 3305.57   395.9 3283.72   405.6 3279.66
     435 3280.14   450.9 3281.24   473.6  3277.4   522.1  3285.3   573.9 3284.73
   632.5  3306.6   658.7 3312.26   711.1 3328.13   783.1 3346.69   812.6 3352.55
   855.1 3365.59   874.8 3368.65   891.1 3377.04   950.1 3396.62   976.5 3414.72
   995.9 3416.96 1006.29 3426.91  1015.6 3434.61  1038.5 3438.37  1051.6 3448.61
#Mann= 5 ,-1 , 0
       0     .12       0   405.6     .04       0     435     .12       0
   976.5    .016       0 1006.29     .12       0
Bank Sta=405.6,435
XS Rating Curve= 0 ,0
Exp/Cntr=0.3,0.1

Type RM Length L Ch R = 1 ,12184   ,289.7,289.7,289.7
XS GIS Cut Line= 2
2124648.85337642405239.1842505062125601.24148786405300.991148594
#Sta/Elev= 30
       0 3477.26    21.7 3467.23    80.9 3447.93    97.4 3437.86   110.5 3435.05
   153.2 3404.77   186.1 3389.18   205.9 3385.47   297.9 3349.28   337.4 3337.09
   393.3 3329.63   432.7 3308.59   491.9 3289.35   547.8 3275.52   569.5 3266.14
   577.4 3265.11   597.1 3265.79   610.2 3272.22   633.3 3272.82   659.6 3291.88
   702.3 3301.16   735.2 3303.57   787.8 3319.99   820.7 3334.03   833.8 3335.37
   853.5 3343.12   863.4 3343.74   922.6 3369.43   937.9 3374.13   954.4 3386.32
#Mann= 3 , 0 , 0
       0     .12       0   569.5     .04       0   597.1     .12       0
Bank Sta=569.5,597.1
XS Rating Curve= 0 ,0
Exp/Cntr(USF)=0,0
Exp/Cntr=0.3,0.1

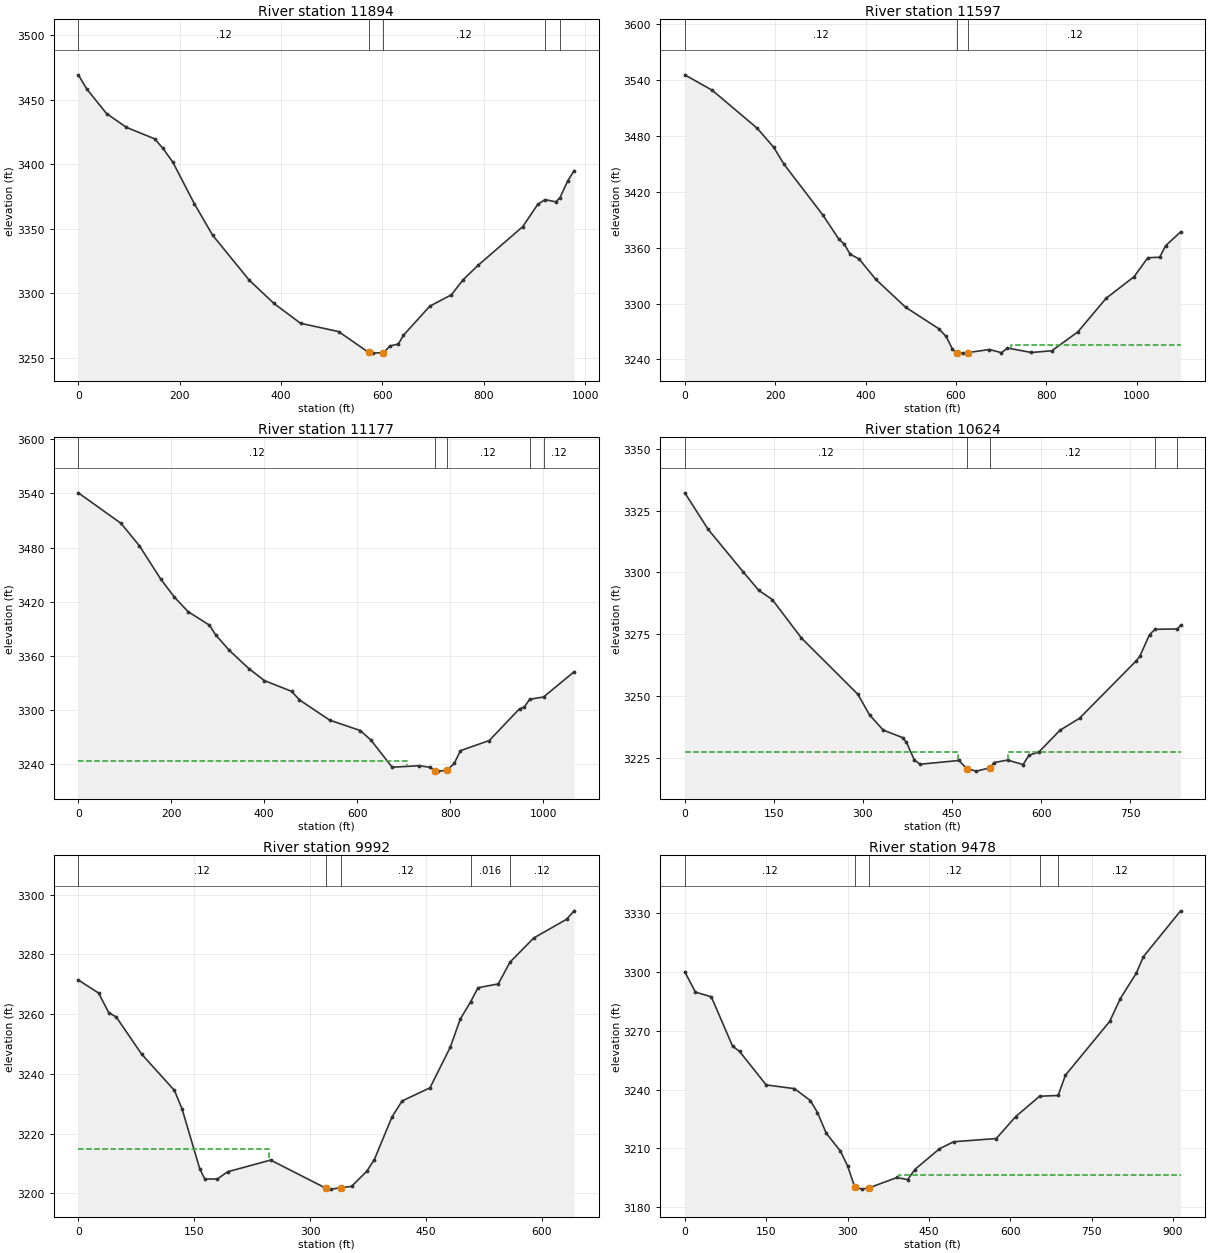
Type RM Length L Ch R = 1 ,11894   ,296.8,296.8,296.8
XS GIS Cut Line= 2
     2124694.364      405521.894     2125670.726      405584.168
#Sta/Elev= 30
       0 3469.12    16.4 3458.28    55.6 3439.17    94.9 3428.46   150.5 3419.61
   166.9 3412.26   186.5 3401.51     229 3369.32     265    3345     337 3310.32
   386.1 3292.14   438.5 3276.84   513.7 3270.39   572.6 3254.36   582.4 3253.73
   602.1 3254.16   615.2 3259.31   631.5 3260.78   641.3 3267.49   693.7 3290.12
   736.2 3298.88   759.1 3310.46   788.6 3321.62   876.9 3351.61   906.4 3368.78
  920.95 3372.55   942.4 3370.81  950.54 3374.11   965.3 3386.73   978.4 3395.02
#Mann= 5 ,-1 , 0
       0     .12       0   572.6     .04       0   602.1     .12       0
  920.95    .016       0  950.54     .12       0
Bank Sta=572.6,602.1
XS Rating Curve= 0 ,0
Exp/Cntr=0.3,0.1

Type RM Length L Ch R = 1 ,11597   ,420.3,420.3,420.3
XS GIS Cut Line= 3
2124584.23707387405742.0676485852125443.91483819405868.490849219
2125671.47659933 405885.34727597
#Sta/Elev= 30
       0  3545.9    60.7 3529.31   160.2 3488.54   196.7 3468.02   219.9 3449.55
   306.1 3394.84   340.8 3369.32   352.7 3364.11   365.8 3353.13   385.7 3347.99
   422.7 3326.08   488.5 3296.21   561.4 3273.25   577.9 3264.96   592.3 3251.12
   601.2 3246.96   615.5 3246.84     627 3247.48   674.2 3250.73   700.7 3247.31
     714  3252.3     767 3247.53   812.1 3249.38   869.8 3269.72   932.3 3305.81
   994.1 3328.97  1024.5 3349.32  1050.8 3349.92  1063.9 3362.26  1097.1 3377.14
#Mann= 3 , 0 , 0
       0     .12       0   601.2     .04       0     627     .12       0
#XS Ineff= 2 , 0
                          722.61         3255.14
Permanent Ineff=
       F       F
Bank Sta=601.2,627
XS Rating Curve= 0 ,0
Exp/Cntr(USF)=0,0
Exp/Cntr=0.3,0.1

Type RM Length L Ch R = 1 ,11177   ,552.7,552.7,552.7
XS GIS Cut Line= 3
      2124560.92      406115.718       2125141.4      406177.992
     2125619.573      406246.938
#Sta/Elev= 30
       0 3540.57    91.8  3506.8   131.2 3482.12   177.1 3445.22   206.6 3425.15
   236.2 3409.02   282.1 3394.06   295.2 3383.54   324.7 3366.17   367.3 3345.84
   400.1 3332.76   459.2 3320.72   475.6 3311.36   541.2 3288.82   606.7 3277.38
   629.5 3266.88   675.2  3236.8     734 3238.41   756.8 3236.69   766.6 3232.97
   773.1 3232.44   792.7 3233.28     809 3240.96   822.1 3255.08   884.1  3266.3
   949.4 3301.52   959.2 3303.16  971.21 3311.96 1001.05 3314.54  1066.9  3342.5
#Mann= 5 ,-1 , 0
       0     .12       0   766.6     .04       0   792.7     .12       0
  971.21    .016       0 1001.05     .12       0
#XS Ineff= 2 , 0
          706.96 3243.75
Permanent Ineff=
       F       F
Bank Sta=766.6,792.7
XS Rating Curve= 0 ,0
Exp/Cntr=0.3,0.1

Type RM Length L Ch R = 1 ,10624   ,631.8,631.8,631.8
XS GIS Cut Line= 2
     2124818.911      406780.712     2125648.485      406687.301
#Sta/Elev= 30
       0 3332.23    39.3 3317.46    98.2 3300.28   124.4 3292.81   147.3 3289.04
   196.4 3273.48   291.4 3250.72     311 3242.41   333.9 3236.25   366.7 3233.19
   373.2 3231.31   386.3 3224.22   396.1 3222.42   461.6 3223.94   474.7 3220.62
   491.1 3219.63     514 3220.99   520.5 3223.09   543.4  3224.1   569.6 3222.29
   579.5 3226.09   595.8 3227.29   631.8 3236.19   664.6 3241.03   759.5 3264.12
   766.1 3266.09   782.4 3274.83   791.7 3277.02  829.27 3277.16   834.8  3278.6
#Mann= 5 ,-1 , 0
       0     .12       0   474.7     .04       0     514     .12       0
   791.7    .016       0  829.27     .12       0
#XS Ineff= 2 , 0
          460.69 3227.19  544.85         3227.44
Permanent Ineff=
       F       F
Bank Sta=474.7,514
XS Rating Curve= 0 ,0
Exp/Cntr=0.3,0.1

Type RM Length L Ch R = 1 ,9992    ,514.4,514.4,514.4
XS GIS Cut Line= 2
     2125475.009       407376.76      2125837.53      406847.434
#Sta/Elev= 30
       0 3271.43    26.2 3267.08    39.3 3260.52    49.1 3259.04    81.8 3246.66
   124.4 3234.46   134.2  3228.3   157.1 3208.25   163.7 3204.79     180 3204.84
   193.1 3207.23   248.8 3211.16   320.8 3201.68   327.3 3201.43   340.4 3201.92
   353.5 3202.35   373.2  3207.4     383  3211.3   405.9 3225.62     419 3230.96
     455 3235.34   481.2 3248.88   494.3 3258.41  507.61 3264.12   517.2 3268.85
   543.4 3270.12   558.6 3277.42   589.2 3285.47   631.8 3291.77   641.6 3294.59
#Mann= 5 ,-1 , 0
       0     .12       0   320.8     .04       0   340.4     .12       0
  507.61    .016       0   558.6     .12       0
#XS Ineff= 2 , 0
          246.51  3214.7
Permanent Ineff=
       F       F
Bank Sta=320.8,340.4
XS Rating Curve= 0 ,0
Exp/Cntr=0.3,0.1

Type RM Length L Ch R = 1 ,9478    ,520.8,520.8,520.8
XS GIS Cut Line= 3
     2125790.825      407781.539     2126046.592      407372.312
     2126262.326       406998.67
#Sta/Elev= 30
       0 3300.06    19.6 3289.68    48.9  3287.3      88 3262.16   101.1 3259.39
     150 3242.35   202.2 3240.45   231.5 3234.36   244.6 3228.26   260.8 3217.68
   286.9 3208.59     300  3201.1     313 3190.53   326.1 3189.19   339.1 3189.79
   391.3 3195.13   410.8 3194.02   423.9 3199.18   469.5 3209.78   495.6 3213.37
   574.1 3214.99     610 3226.21  654.09 3236.57  688.19 3236.97   701.6 3247.28
   783.3 3274.76   802.9 3286.42   832.3 3299.36   845.4 3307.78     914 3331.14
#Mann= 5 ,-1 , 0
       0     .12       0     313     .04       0   339.1     .12       0
  654.09    .016       0  688.19     .12       0
#XS Ineff= 2 , 0
                          394.57         3196.44
Permanent Ineff=
       F       F
Bank Sta=313,339.1
XS Rating Curve= 0 ,0
Exp/Cntr=0.3,0.1