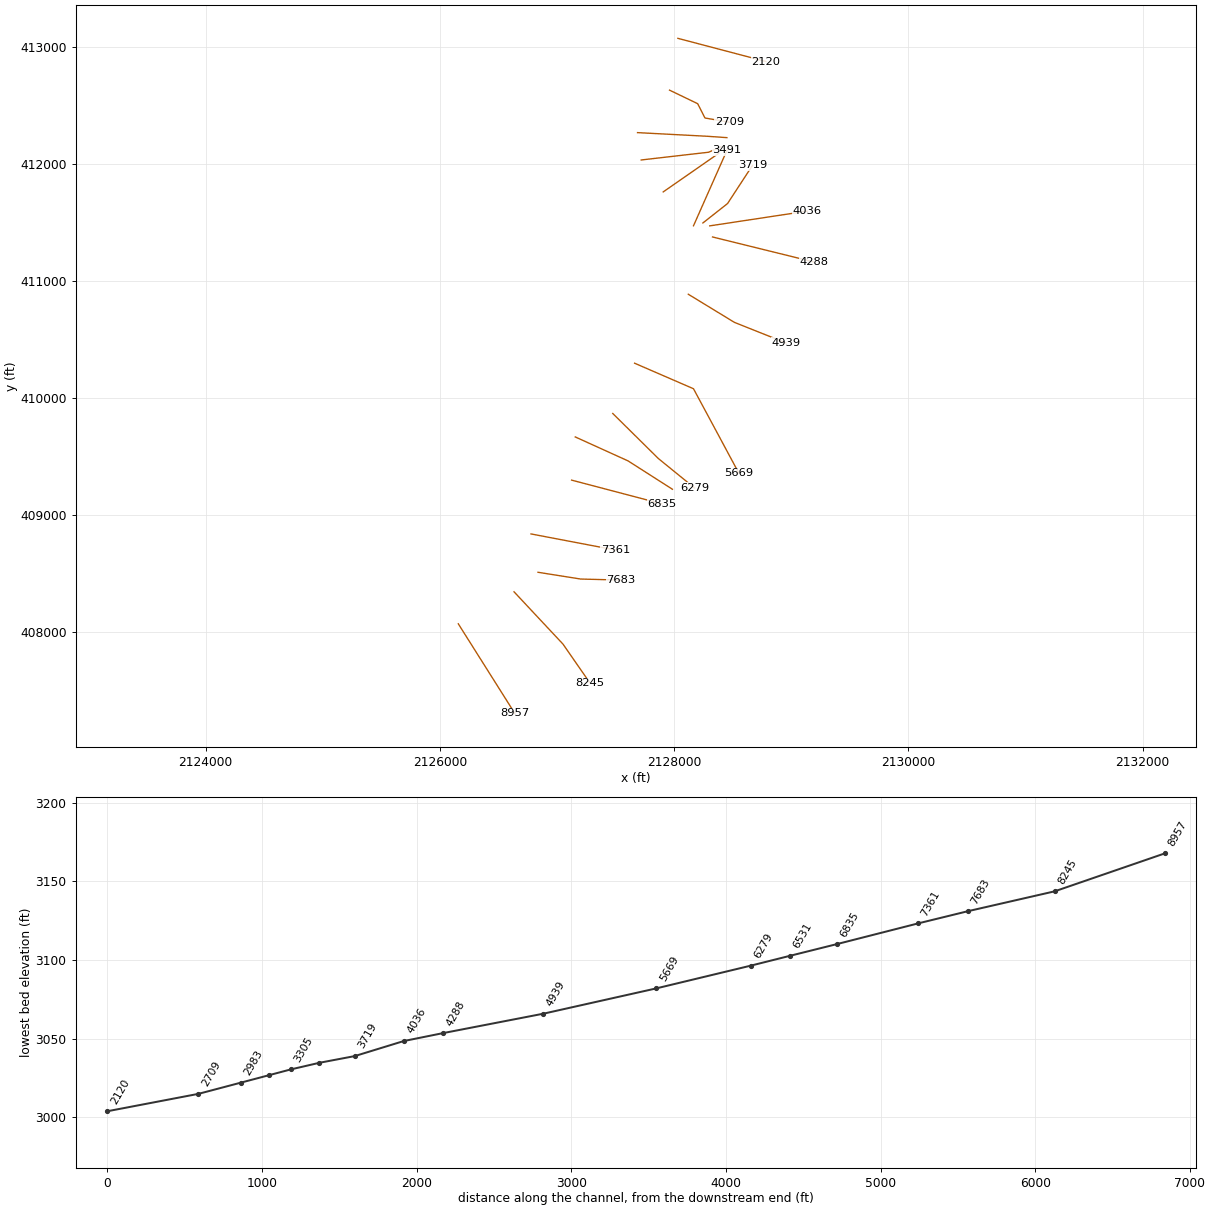
HEC-RAS study COLDKNOBFK.prj: COLDKNOBFK

--- COLDKNOBFK.g01 (geometry) --- (continued)

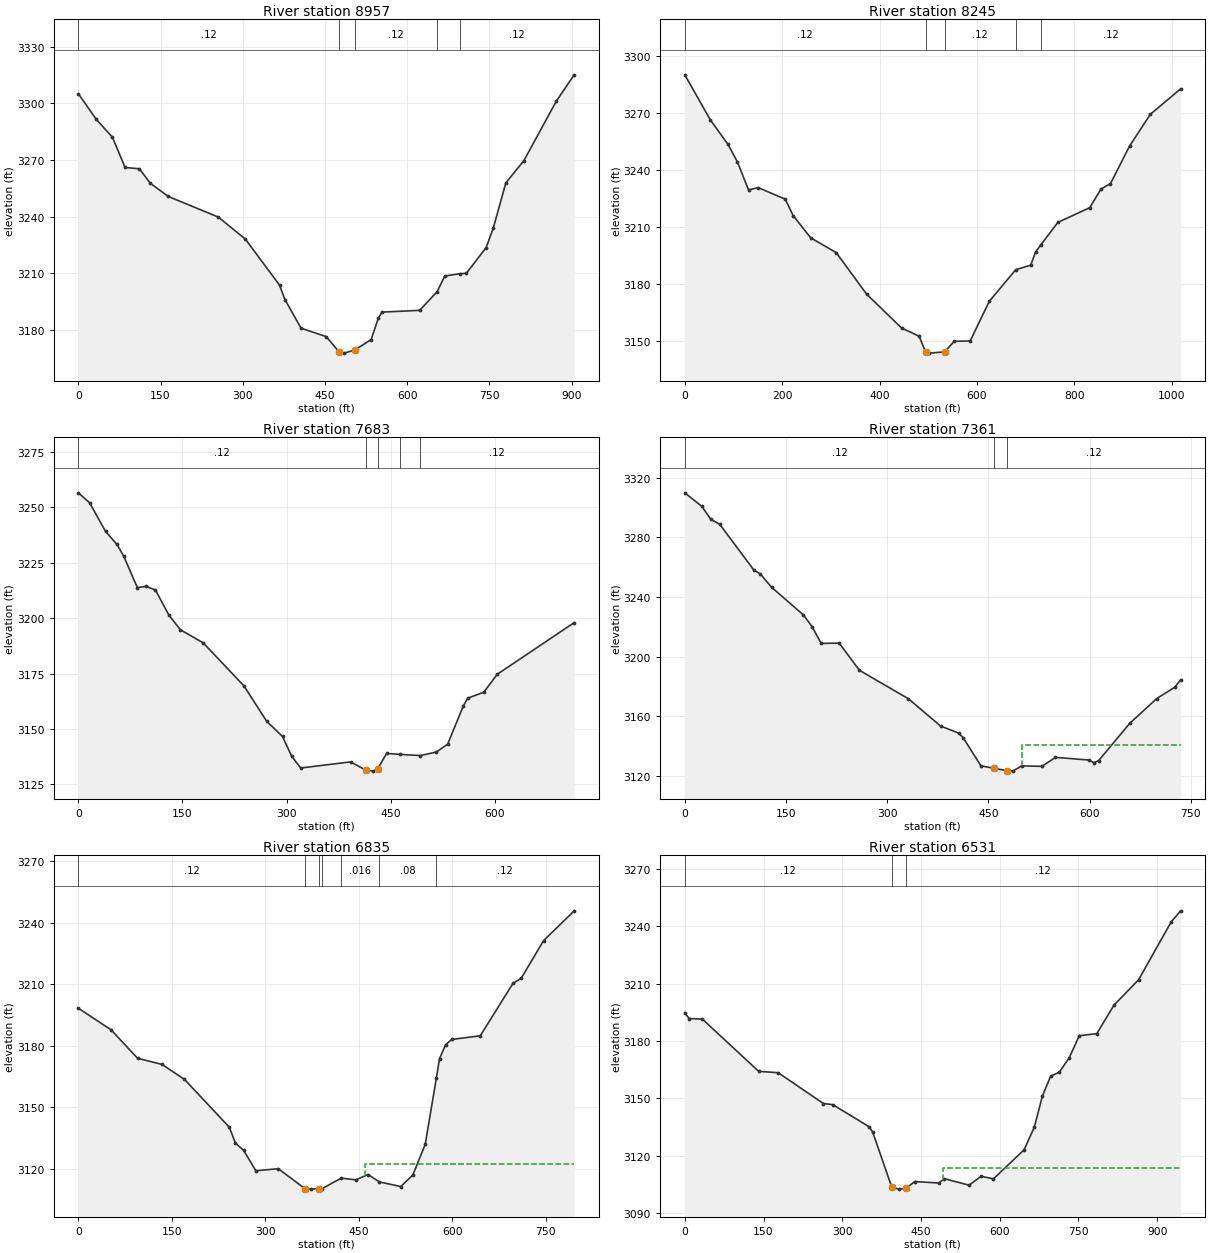
Type RM Length L Ch R = 1 ,8957    ,711.9,711.9,711.9
XS GIS Cut Line= 2
     2126157.795       408072.89     2126640.416      407307.814
#Sta/Elev= 30
       0 3305.14    32.8 3291.52    62.3 3282.06    85.2 3266.07   111.4 3265.37
   131.1 3257.75   163.9 3250.74   255.6 3239.76   304.8 3228.11   367.1 3203.74
   376.9 3196.12   406.4 3180.96   452.3 3176.49   475.2  3168.6   485.1 3167.75
   504.5 3169.42   534.2 3174.92   547.3 3186.22   553.9 3189.47   622.7  3190.4
  654.71 3200.35   668.6 3208.59  695.85 3209.79   707.9    3210     744 3223.66
   757.1 3233.99     780 3257.95   812.8 3269.64   871.8 3301.05   904.6 3315.12
#Mann= 5 ,-1 , 0
       0     .12       0   475.2     .04       0   504.5     .12       0
  654.71    .016       0  695.85     .12       0
Bank Sta=475.2,504.5
XS Rating Curve= 0 ,0
Exp/Cntr=0.3,0.1

Type RM Length L Ch R = 1 ,8245    ,561.9,561.9,561.9
XS GIS Cut Line= 3
     2126633.744       408346.45     2127051.867      407899.414
     2127283.169      407565.805
#Sta/Elev= 30
       0 3290.25    52.4 3266.52    88.4 3253.73     108 3244.41   130.9  3229.6
   150.6 3230.86   206.2 3224.74   222.6 3216.05   258.6 3204.37     311 3196.57
   373.2 3174.75   445.2 3156.86   481.2 3152.54   494.3 3144.17   500.8 3143.65
   533.5  3144.3   553.2 3149.89   585.9 3150.04   625.2 3170.99  679.45 3187.58
   710.3    3190   720.1 3196.86  731.29 3200.79     766 3212.53   831.4 3220.26
   854.4 3230.07     874 3232.96   913.3 3252.79   955.8 3269.44    1018 3282.88
#Mann= 5 ,-1 , 0
       0     .12       0   494.3     .04       0   533.5     .12       0
  679.45    .016       0  731.29     .12       0
Bank Sta=494.3,533.5
XS Rating Curve= 0 ,0
Exp/Cntr=0.3,0.1

Type RM Length L Ch R = 1 ,7683    ,322.5,322.5,322.5
XS GIS Cut Line= 3
     2126838.357      408513.254     2127203.103      408455.429
     2127547.832      408446.532
#Sta/Elev= 30
       0 3256.57    16.3 3252.06    39.2 3239.15    55.6 3233.28    65.4 3227.98
      85 3213.83      98 3214.39   111.1 3212.68   130.7 3201.26   147.1 3194.77
   179.8  3188.9   238.6 3169.45   271.3  3153.5   294.1 3146.64   307.2  3137.8
   320.3 3132.41   392.1 3135.17   413.7 3131.51   424.6    3131   431.1 3132.05
   444.1 3138.97  463.22 3138.55  492.77 3138.03   515.7 3139.62     532 3143.16
   554.7 3160.55   561.2 3163.95     584  3166.6   603.5 3174.72   714.2    3198
#Mann= 5 ,-1 , 0
       0     .12       0   413.7     .04       0   431.1     .12       0
  463.22    .016       0  492.77     .12       0
Bank Sta=413.7,431.1
XS Rating Curve= 0 ,0
Exp/Cntr=0.3,0.1

Type RM Length L Ch R = 1 ,7361    ,525.5,525.5,525.5
XS GIS Cut Line= 2
2126778.38195599408840.8407663552127500.39890184408703.179947886
#Sta/Elev= 30
       0 3309.85    25.2 3300.81    38.5  3292.1    51.9  3288.7   102.3 3258.09
     112 3255.43   128.7  3246.5   175.8    3228   188.8 3220.02   202.2 3208.87
   228.9 3209.06   258.9 3190.84   331.5 3171.75   379.2 3153.45   405.9 3148.75
   412.6 3145.68   438.9  3126.8   458.73125.132   477.1 3123.56   486.1 3123.23
   499.4 3126.75   529.5 3126.44   549.5 3132.46   599.6 3130.65   606.3  3128.9
   613.3  3130.2   659.7 3155.34   699.7 3171.92   726.5 3179.55     735 3184.45
#Mann= 3 , 0 , 0
       0     .12       0   458.7     .04       0   477.1     .12       0
#XS Ineff= 2 , 0
                          500.45         3140.79
Permanent Ineff=
       F       F
Bank Sta=458.7,477.1
XS Rating Curve= 0 ,0
Exp/Cntr(USF)=0,0
Exp/Cntr=0.3,0.1

Type RM Length L Ch R = 1 ,6835    ,304.3,304.3,304.3
XS GIS Cut Line= 2
     2127125.261      409300.571     2127894.785      409098.182
#Sta/Elev= 30
       0 3198.25    52.4 3187.76      95 3173.87   134.2 3170.85   170.3 3163.58
   242.3 3140.23   252.1 3132.52   265.2 3128.99   284.9 3119.01   320.9 3120.02
   363.5 3110.34   373.3 3110.06   385.9 3110.28  391.35 3110.35  421.89 3115.42
   445.3 3114.59     465 3117.19  482.97 3113.59   517.4 3111.32     537 3117.03
   556.7 3131.94  574.59 3164.23   579.6 3173.63   589.4 3180.49   599.2    3183
   645.1 3184.83   697.5 3210.36   710.6 3212.78   746.6 3231.18   795.7 3245.72
#Mann= 7 ,-1 , 0
       0     .12       0   363.5     .04       0   385.9     .12       0
  391.35     .08       0  421.89    .016       0  482.97     .08       0
  574.59     .12       0
#XS Ineff= 2 , 0
                           459.8         3122.36
Permanent Ineff=
       F       F
Bank Sta=363.5,385.9
XS Rating Curve= 0 ,0
Exp/Cntr=0.3,0.1

Type RM Length L Ch R = 1 ,6531    ,251.7,251.7,251.7
XS GIS Cut Line= 3
2127156.48044892409669.5079228322127607.48515732409464.693858009
 2127986.0808529409222.640872309
#Sta/Elev= 30
       0 3194.76     8.2 3191.73    33.5 3191.44   140.7 3164.16   177.9 3163.42
   264.1 3147.33     282 3146.73   350.5 3135.31   357.8 3132.53   394.53103.537
   408.3  3102.6   421.53103.011   438.1 3106.56   483.9 3105.79   494.7 3108.06
   541.4 3104.68   564.7 3109.29   588.1 3107.97   646.5 3123.16     666 3135.04
   681.5 3151.36   697.1 3161.64   713.6 3163.69   732.6 3171.32   751.6 3182.78
   784.9 3183.82   817.8 3198.75   864.6    3212   926.9 3242.32   944.7 3248.01
#Mann= 3 ,-1 , 0
       0     .12       0   394.5     .04       0   421.5     .12       0
#XS Ineff= 2 , 0
                          491.03         3113.72
Permanent Ineff=
       F       F
Bank Sta=394.5,421.5
XS Rating Curve= 0 ,0
Exp/Cntr(USF)=0,0
Exp/Cntr=0.3,0.1

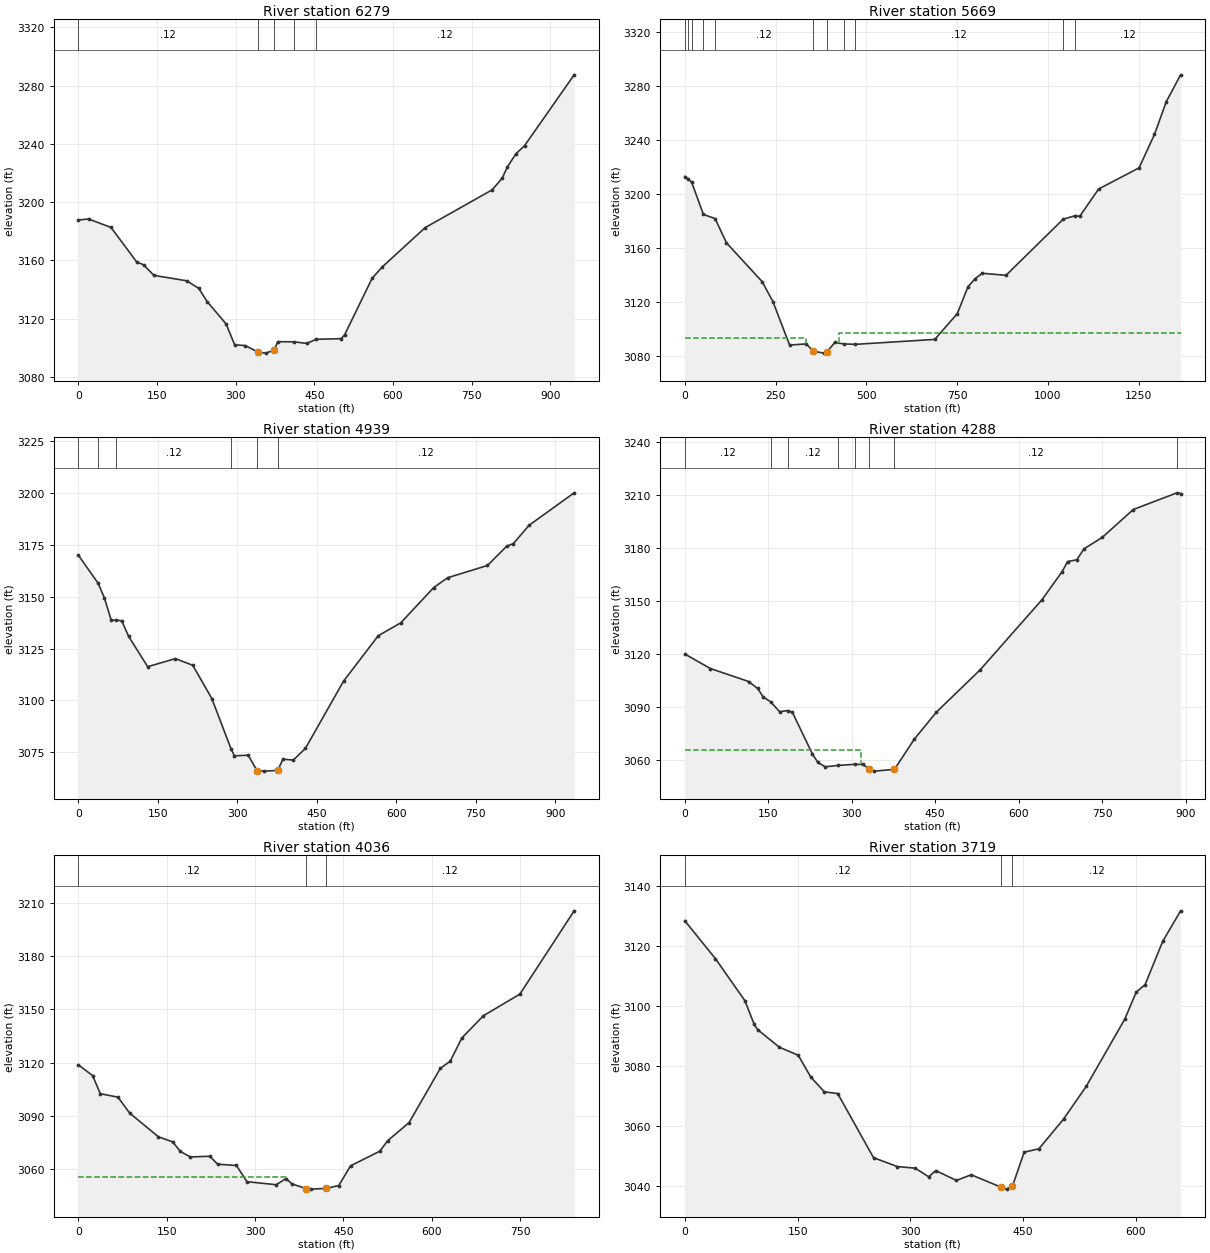
Type RM Length L Ch R = 1 ,6279    ,610.1,610.1,610.1
XS GIS Cut Line= 3
     2127476.662       409869.93     2127865.873      409485.168
     2128175.017      409233.849
#Sta/Elev= 30
       0 3187.82    19.7 3188.46    62.3 3182.68   111.4 3158.96   124.5 3157.02
   144.2 3149.77   206.5 3146.06   229.4 3140.96   245.8 3131.75   281.8 3116.46
   298.2 3102.09   317.9  3101.6   343.2  3097.1   357.2 3096.39   373.6  3098.4
   380.2 3104.26  411.86 3104.14   435.9 3103.07  453.39 3105.88   501.4 3106.33
     508 3109.03   560.4  3147.8     580 3155.68   661.6 3182.58     789 3208.43
   808.5  3216.5   818.3 3224.21   834.7 3233.28     851 3238.77   945.7 3287.45
#Mann= 5 ,-1 , 0
       0     .12       0   343.2     .04       0   373.6     .12       0
  411.86    .016       0  453.39     .12       0
Bank Sta=343.2,373.6
XS Rating Curve= 0 ,0
Exp/Cntr=0.3,0.1

Type RM Length L Ch R = 1 ,5669    ,730,730,730
XS GIS Cut Line= 3
     2127663.483      410299.174     2128166.121      410081.216
     2128553.107      409360.621
#Sta/Elev= 30
       0 3213.03    9.06 3211.31   19.04 3208.66   51.23 3184.89   83.42  3181.8
   114.8 3163.79   213.2 3134.98   242.8 3120.16   288.7 3087.97   334.6  3088.8
   354.3 3083.37   383.6 3081.96   390.4 3082.61   413.4 3089.87  437.55  3088.8
  469.75 3088.49   688.5 3092.13   750.7  3111.3   780.2  3131.3   799.8 3137.24
   819.4 3141.21   884.8 3139.71 1042.12 3181.31 1075.64 3184.01  1087.7 3183.45
    1140 3203.77  1251.3 3219.43  1293.8 3244.28  1326.5 3268.67  1365.8 3288.48
#Mann= 11 ,-1 , 0
       0     .12       0    9.06     .08       0   19.04     .06       0
   51.23     .08       0   83.42     .12       0   354.3     .04       0
   390.4     .12       0  437.55    .016       0  469.75     .12       0
 1042.12    .016       0 1075.64     .12       0
#XS Ineff= 2 , 0
          333.26 3093.24  425.34         3097.07
Permanent Ineff=
       F       F
Bank Sta=354.3,390.4
XS Rating Curve= 0 ,0
Exp/Cntr=0.3,0.1

Type RM Length L Ch R = 1 ,4939    ,651.6,651.6,651.6
XS GIS Cut Line= 3
     2128121.639       410888.55     2128515.298      410648.351
     2128955.662      410472.651
#Sta/Elev= 30
       0 3170.09   37.35 3156.52    49.1 3149.49    62.1 3138.64   71.95 3138.74
    81.8 3138.43    94.8 3130.94   130.8 3116.26   183.2 3120.17   215.9 3116.94
   251.8  3100.9  287.85 3076.76   294.4 3073.27   320.5 3073.55   336.9 3066.18
     350 3065.88   376.1 3066.22   385.9 3071.65   405.6 3071.24   428.4 3076.87
   500.4 3109.34   565.8 3131.22   608.3 3137.44   670.4 3154.46   696.6 3159.18
   771.8  3165.1   807.8 3174.36   820.8  3175.7   850.3  3184.5   935.3 3200.15
#Mann= 6 ,-1 , 0
       0     .12       0   37.35     .08       0   71.95     .12       0
  287.85    .016       0   336.9     .04       0   376.1     .12       0
Bank Sta=336.9,376.1
XS Rating Curve= 0 ,0
Exp/Cntr=0.3,0.1

Type RM Length L Ch R = 1 ,4288    ,251.4,251.4,251.4
XS GIS Cut Line= 2
     2128328.477      411377.843     2129193.636      411164.333
#Sta/Elev= 30
       0 3119.76    45.9 3111.55   114.7  3104.2     131 3100.25   140.9 3095.47
  154.44 3092.67   170.4  3087.1  184.86 3087.74   193.3 3086.82   229.3  3063.2
   239.2 3058.38   252.3 3055.93  276.13 3056.74  306.55 3057.34   321.1 3057.25
   330.9 3054.45   340.7 3053.48   376.8 3054.47   412.8 3071.71   452.1 3086.84
   530.7 3110.76   642.1 3150.54   678.2 3166.42     688 3172.09   704.4 3173.06
   717.5 3179.28   750.2 3185.73   805.9 3201.52  884.58 3210.97   891.1 3210.58
#Mann= 8 ,-1 , 0
       0     .12       0  154.44     .08       0  184.86     .12       0
  276.13    .016       0  306.55     .12       0   330.9     .04       0
   376.8     .12       0  884.58    .016       0
#XS Ineff= 2 , 0
          316.72 3065.48
Permanent Ineff=
       F       F
Bank Sta=330.9,376.8
XS Rating Curve= 0 ,0
Exp/Cntr=0.3,0.1

Type RM Length L Ch R = 1 ,4036    ,316.9,316.9,316.9
XS GIS Cut Line= 2
2128304.78311718411472.649830443 2129137.2337185411598.778709431
#Sta/Elev= 30
       0 3118.72    24.2 3112.64    37.4  3102.4    67.3 3100.44    87.2 3091.44
     136 3078.05   160.2 3075.19   173.4 3069.76   190.1 3066.68   223.3 3067.05
   236.5 3062.56   268.5 3061.84   286.3  3052.7   336.1 3050.98   352.7 3054.49
   362.6 3051.45   386.7 3048.83   395.3 3048.49   421.2 3048.91   442.3 3050.53
   462.2 3061.64     512 3069.93   525.2 3075.81   561.7 3086.08   614.8 3116.78
   631.4 3120.69   651.3 3133.89   687.8 3146.42   749.8 3158.65     842 3205.71
#Mann= 3 , 0 , 0
       0     .12       0   386.7     .04       0   421.2     .12       0
#XS Ineff= 2 , 0
          351.89  3055.3
Permanent Ineff=
       F       F
Bank Sta=386.7,421.2
XS Rating Curve= 0 ,0
Exp/Cntr(USF)=0,0
Exp/Cntr=0.3,0.1

Type RM Length L Ch R = 1 ,3719    ,228.7,228.7,228.7
XS GIS Cut Line= 3
2128246.28870457411497.4580685552128456.68860752411663.171266457
2128670.81240256411990.873770173
#Sta/Elev= 30
       0 3128.47    40.8 3115.79    79.8 3101.85    92.3 3093.89    96.8 3092.14
   125.8 3086.27   150.8  3083.6   167.5 3076.33   185.6 3071.38   203.3 3070.82
     251 3049.41   282.8 3046.45   306.3 3045.93   324.3 3043.05   333.7 3045.12
   361.2 3041.83   380.8 3043.72     420 3039.64   427.8 3038.93   435.7  3039.9
   435.7 3039.94   451.3 3051.27   470.9 3052.39   503.6 3062.29   533.7 3073.18
     585 3095.63   600.3 3104.68     612 3107.12   635.5  3121.6   659.3 3131.78
#Mann= 3 , 0 , 0
       0     .12       0     420     .04       0   435.7     .12       0
Bank Sta=420,435.7
XS Rating Curve= 0 ,0
Exp/Cntr(USF)=0,0
Exp/Cntr=0.3,0.1

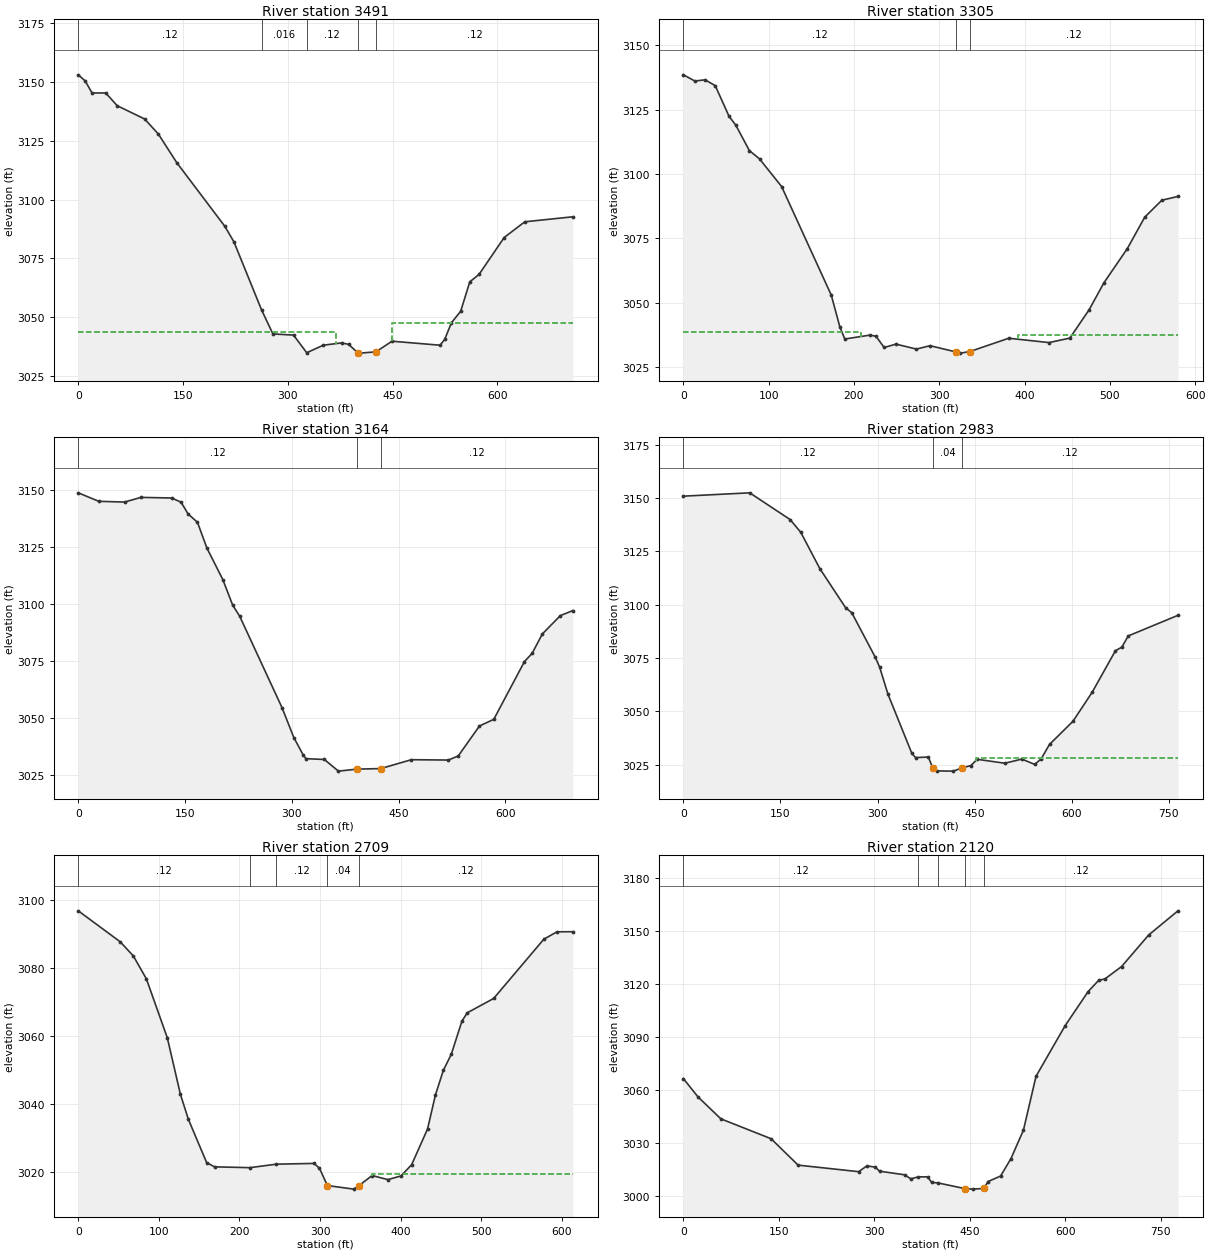
Type RM Length L Ch R = 1 ,3491    ,186.1,186.1,186.1
XS GIS Cut Line= 2
     2128166.121      411473.477     2128453.024      412120.679
#Sta/Elev= 30
       0  3153.1     9.8 3150.55    19.7 3145.37    39.3 3145.38    55.7 3139.97
      95  3134.3   114.7 3127.88   140.9 3115.76   209.8 3088.63   222.9 3081.96
  262.35 3053.06   278.6 3042.84   308.1 3042.34  326.97 3034.84   350.7 3038.04
   376.9 3039.02   386.8 3038.42   399.9 3034.89   403.1 3034.67   426.1 3035.21
     449 3039.74   517.8 3038.04   524.4 3040.47   534.2 3047.64   547.3 3052.47
   560.4 3065.01   573.6 3068.15   609.6 3083.87   639.1 3090.56   707.9 3092.69
#Mann= 5 ,-1 , 0
       0     .12       0  262.35    .016       0  326.97     .12       0
   399.9     .04       0   426.1     .12       0
#XS Ineff= 2 , 0
          368.55 3043.68  449.17         3047.44
Permanent Ineff=
       F       F
Bank Sta=399.9,426.1
XS Rating Curve= 0 ,0
Exp/Cntr=0.3,0.1

Type RM Length L Ch R = 1 ,3305    ,141.1,141.1,141.1
XS GIS Cut Line= 2
2127907.47714837411762.7462521162128383.61366655412093.834559459
#Sta/Elev= 30
       0 3138.59    13.5 3136.18    25.5 3136.65    37.4 3134.38    53.5 3122.49
    61.5 3119.02    77.4 3109.15    89.4 3105.88   115.2 3095.17   173.4 3052.99
   183.5 3040.62   189.3 3035.92   218.9 3037.44   225.9 3036.98   235.4 3032.62
   249.3 3033.93   273.3    3032   289.2 3033.32   319.23030.923   324.9 3030.43
   336.1 3031.06   381.5 3036.22   428.7 3034.53   453.1 3036.26   475.8  3047.3
     493 3057.71   520.6 3071.09     541 3083.29     561 3089.85   579.9 3091.33
#Mann= 3 , 0 , 0
       0     .12       0   319.2     .04       0   336.1     .12       0
#XS Ineff= 2 , 0
           207.8 3038.62  392.87         3037.49
Permanent Ineff=
       F       F
Bank Sta=319.2,336.1
XS Rating Curve= 0 ,0
Exp/Cntr(USF)=0,0
Exp/Cntr=0.3,0.1

Type RM Length L Ch R = 1 ,3164    ,180.7,180.7,180.7
XS GIS Cut Line= 3
2127719.37383254412035.6751319262128295.51809459412101.853864728
2128400.62549374412148.568264354
#Sta/Elev= 30
       0 3148.57    28.8 3144.86      65 3144.53    88.2 3146.58   131.2  3146.3
   144.4 3144.48   154.3 3139.33   167.5 3135.67   180.7 3124.44   203.1  3110.6
     217 3099.39   226.9 3094.52   286.4 3054.48   302.9 3041.44   316.1 3033.82
   319.9 3032.21   345.8 3031.85   365.6 3026.75     392 3027.63   425.1 3027.87
     468 3031.75   520.2  3031.6     534 3033.41   563.8 3046.52   583.9 3049.42
     627 3074.72   637.8  3078.3   652.1 3086.78   677.4 3094.82     695 3097.04
#Mann= 3 , 0 , 0
       0     .12       0     392     .04       0   425.1     .12       0
Bank Sta=392,425.1
XS Rating Curve= 0 ,0
Exp/Cntr(USF)=0,0
Exp/Cntr=0.3,0.1

Type RM Length L Ch R = 1 ,2983    ,274.2,274.2,274.2
XS GIS Cut Line= 3
2127688.23089946412269.2471300522128283.83949468412238.104196968
   2128451.23276412226.425597062
#Sta/Elev= 30
       0 3150.83   102.5 3152.39   164.9 3139.88   181.4 3133.91   210.9 3116.88
   250.6 3098.62   260.2 3096.23   296.4 3075.46   303.2  3070.8   316.1 3058.11
   353.1 3030.33   358.8 3028.39   378.5 3028.64   385.1 3023.73   391.6 3022.15
     417 3022.05   430.9  3023.6   444.2 3024.65   454.1 3027.58   496.8 3025.75
     523 3027.68   542.8 3025.22   552.6  3027.7   565.8 3034.57   601.9 3045.37
   631.5 3058.91   667.7 3078.48   677.5 3080.11   687.4 3085.37   764.2 3095.02
#Mann= 3 , 0 , 0
       0     .12       0   385.1     .04       0   430.9     .12       0
#XS Ineff= 2 , 0
                          451.67         3028.31
Permanent Ineff=
       F       F
Bank Sta=385.1,430.9
XS Rating Curve= 0 ,0
Exp/Cntr(USF)=0,0
Exp/Cntr=0.3,0.1

Type RM Length L Ch R = 1 ,2709    ,588.7,588.7,588.7
XS GIS Cut Line= 4
     2127961.507      412632.212     2128201.706      412516.561
     2128263.979      412394.238     2128470.817      412358.653
#Sta/Elev= 30
       0 3096.87      52 3087.76    68.3  3083.6    84.5 3076.85   110.5 3059.47
   126.8  3042.8   136.6  3035.5   159.3 3022.74   169.1 3021.49   213.1 3021.25
  245.88 3022.28   292.7  3022.5   299.3 3021.06   309.1 3015.99   341.8 3014.93
   348.3 3015.96   364.6 3018.93   384.2 3017.73   400.6 3018.83   413.7 3022.14
   433.4 3032.64   443.2 3042.67     453  3049.9   462.9 3054.66     476 3064.35
   482.6 3066.84   515.4 3071.06   577.7 3088.52     594 3090.69   613.7 3090.72
#Mann= 5 ,-1 , 0
       0     .12       0   213.1    .016       0  245.88     .12       0
   309.1     .04       0   348.3     .12       0
#XS Ineff= 2 , 0
                          364.81         3019.43
Permanent Ineff=
       F       F
Bank Sta=309.1,348.3
XS Rating Curve= 0 ,0
Exp/Cntr=0.3,0.1

Type RM Length L Ch R = 1 ,2120    ,610.9,610.9,610.9
XS GIS Cut Line= 2
     2128032.677        413074.8     2128784.409      412876.859
#Sta/Elev= 30
       0 3066.51      23  3056.1      59 3043.68   137.8 3032.44   180.4 3017.47
   275.5 3013.77   288.6 3017.06   301.8 3016.32   308.3 3014.05   347.7 3011.99
   357.5 3009.72  369.29 3010.82   383.8 3010.83   390.3 3007.66  399.84 3007.42
   442.2  3004.2   455.9 3003.88   472.3 3004.28   478.9 3008.18   498.6 3011.29
     515 3021.22   534.6 3037.36   554.3 3067.79   600.2 3096.54   636.3  3115.8
   652.7  3122.1   662.6 3122.94   688.8 3129.95   731.4 3147.83   777.4 3161.51
#Mann= 5 ,-1 , 0
       0     .12       0  369.29    .016       0  399.84     .12       0
   442.2     .04       0   472.3     .12       0
Bank Sta=442.2,472.3
XS Rating Curve= 0 ,0
Exp/Cntr=0.3,0.1