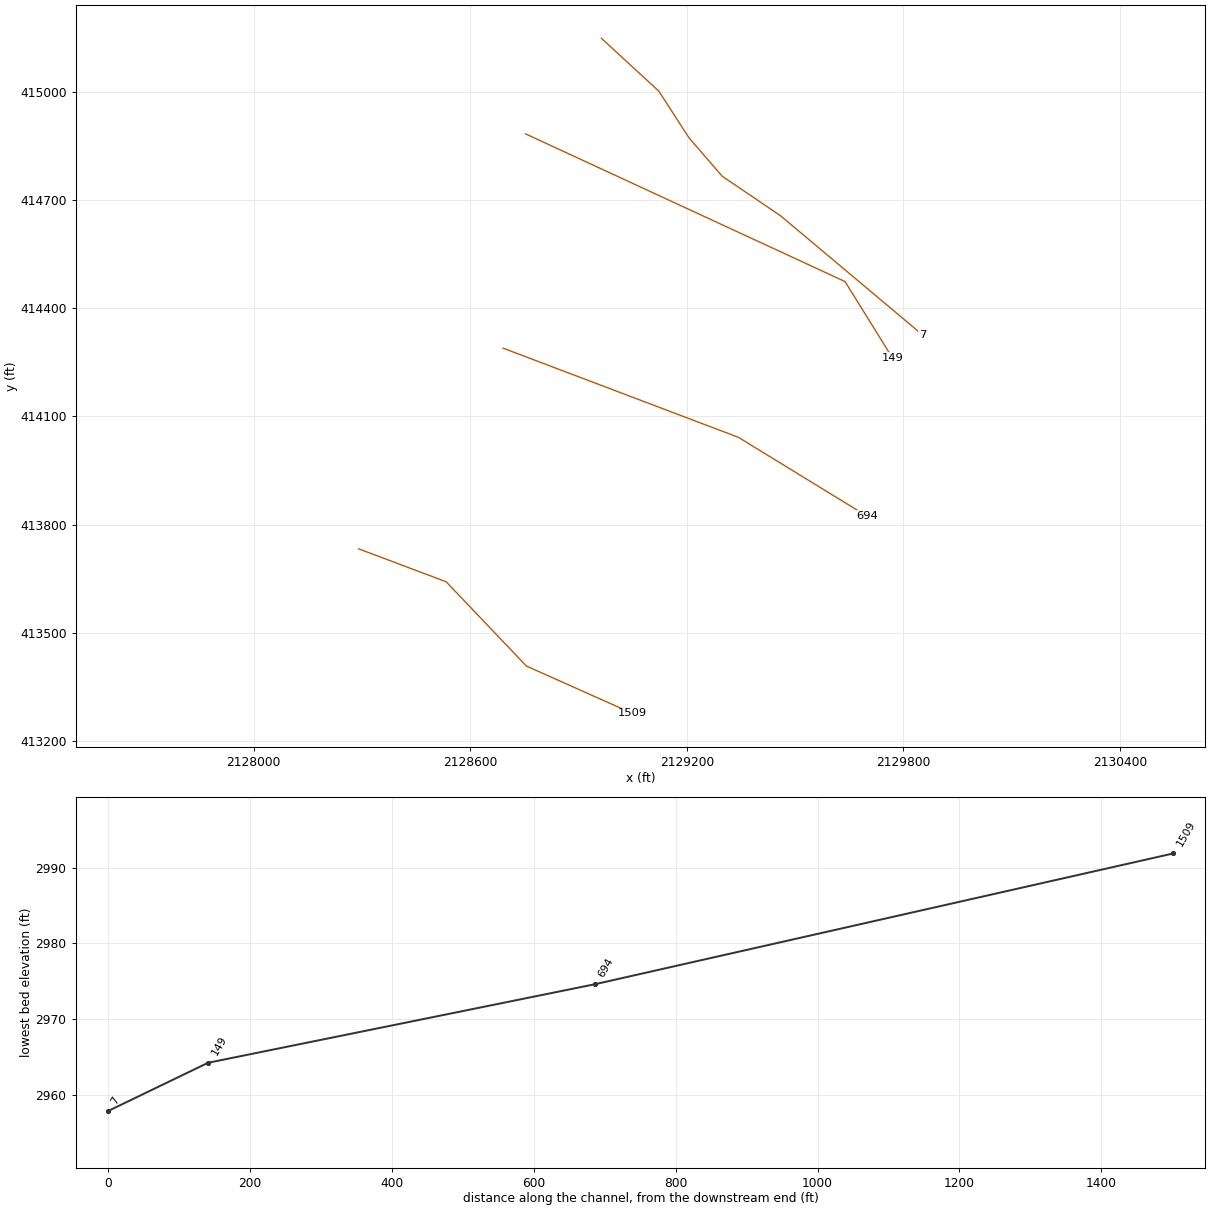
HEC-RAS study COLDKNOBFK.prj: COLDKNOBFK

--- COLDKNOBFK.g01 (geometry) --- (continued)

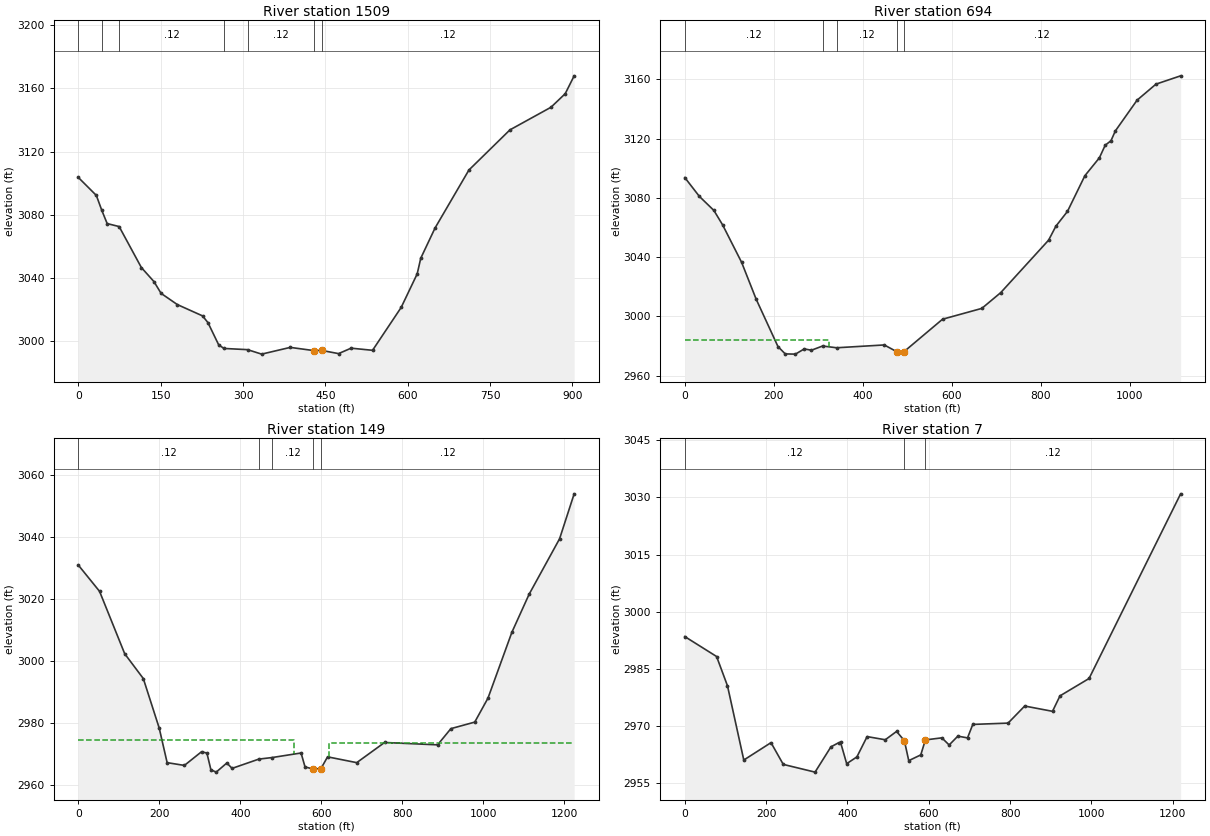
Type RM Length L Ch R = 1 ,1509    ,815.2,815.2,815.2
XS GIS Cut Line= 4
     2128290.668      413733.122      2128533.09      413641.935
     2128755.496      413408.409     2129049.072      413277.189
#Sta/Elev= 30
       0 3103.68    32.8 3092.31   42.79 3082.83    52.5  3074.5   74.35  3072.6
   114.8 3046.68   137.7 3037.79   150.8 3030.31   180.3 3023.24   226.2 3016.08
   236.1  3011.8   255.7  2997.7  265.36 2995.46  308.19  2994.7   333.9 2991.87
     386 2996.13   428.5 2994.13   443.5 2994.19     474  2992.2   496.8 2995.64
   535.9 2994.29     588 3021.41   617.2 3042.66   623.7 3052.56   649.7 3071.68
   711.4 3108.38   786.1 3133.79   860.8 3148.09   886.8 3156.68   903.1    3168
#Mann= 7 ,-1 , 0
       0     .12       0   42.79     .06       0   74.35     .12       0
  265.36    .016       0  308.19     .12       0   428.5     .04       0
   443.5     .12       0
Bank Sta=428.5,443.5
XS Rating Curve= 0 ,0
Exp/Cntr=0.3,0.1

Type RM Length L Ch R = 1 ,694     ,544.7,544.7,544.7
XS GIS Cut Line= 3
     2128690.999      414289.136     2129342.648      414042.266
     2129698.498      413824.308
#Sta/Elev= 30
       0  3093.7    32.7    3081    65.4  3071.5    85.1  3061.7   127.6 3036.55
   160.3 3011.69   209.4 2979.67   225.7 2974.75   248.6  2974.6   268.3  2978.1
   284.6 2977.24   309.6 2980.07  341.18 2978.89   448.2 2980.79   477.3 2976.08
   492.3 2976.21   579.1 2998.14   667.4 3005.45   709.9 3016.08   817.5 3051.49
   833.8 3060.89   859.8 3070.85     899 3094.95   931.6 3107.03   944.6 3115.49
   957.6 3118.53   967.4 3125.13  1016.3 3145.91  1058.7  3156.7  1114.1 3162.31
#Mann= 5 ,-1 , 0
       0     .12       0   309.6    .016       0  341.18     .12       0
   477.3     .04       0   492.3     .12       0
#XS Ineff= 2 , 0
          324.53 2983.92
Permanent Ineff=
       F       F
Bank Sta=477.3,492.3
XS Rating Curve= 0 ,0
Exp/Cntr=0.3,0.1

Type RM Length L Ch R = 1 ,149     ,141.5,141.5,141.5
XS GIS Cut Line= 3
     2128753.272       414882.96     2129638.448      414473.733
     2129769.667      414262.448
#Sta/Elev= 30
       0 3030.86    52.4 3022.42   114.5 3002.33   160.4 2994.35   199.6 2978.43
   219.2 2967.29   261.8  2966.4   304.3 2970.82   317.4 2970.36   327.2 2965.01
   340.3 2964.24   366.5 2967.17   379.6 2965.45  445.59 2968.43  478.13 2968.93
   549.8  2970.4   559.6 2965.91   579.2 2965.27   598.9 2965.38   615.2 2969.16
   687.2 2967.29   755.9 2973.78   886.8 2973.02   919.6 2978.23   978.5 2980.34
  1011.2 2988.06  1070.1 3009.22  1112.6 3021.45  1187.9 3039.33  1223.9  3053.8
#Mann= 5 ,-1 , 0
       0     .12       0  445.59    .016       0  478.13     .12       0
   579.2     .04       0   598.9     .12       0
#XS Ineff= 2 , 0
          531.33 2974.44   619.9         2973.77
Permanent Ineff=
       F       F
Bank Sta=579.2,598.9
XS Rating Curve= 0 ,0
Exp/Cntr=0.3,0.1

Type RM Length L Ch R = 1 ,7       ,6.8,7,6.9
XS GIS Cut Line= 6
2128963.37425904415147.7215411252129122.50240678415001.315238568
2129205.96447248414872.2221200442129297.47507394414766.121872357
2129459.75529484414656.0344158282129852.87029955 414326.28720292
#Sta/Elev= 30
       02993.457  78.2112988.215  104.962980.517 145.0832961.017 211.9562965.588
 242.1722959.872 320.3082957.844 359.3762964.487 378.0012965.548 383.0242965.664
 398.0942960.064 423.2112961.844 448.3272967.179 492.9982966.345 520.8082968.543
 539.9762966.095 550.6992960.856 580.2762962.374 591.6082966.307 632.0992966.851
 650.0492964.975  671.462967.298 695.2472966.838 708.1962970.379 794.983 2970.72
 835.8242975.207   904.22973.818 922.6112977.878 994.1072982.4411219.2673030.953
#Mann= 3 , 0 , 0
       0     .12       0 539.976     .04       0 591.608     .12       0
Bank Sta=539.976,591.608
XS Rating Curve= 0 ,0
Exp/Cntr(USF)=0,0
Exp/Cntr=0.3,0.1
LCMann Table=0

Chan Stop Cuts=-1
Use User Specified Reach Order=0
Composite Channel Slope=5